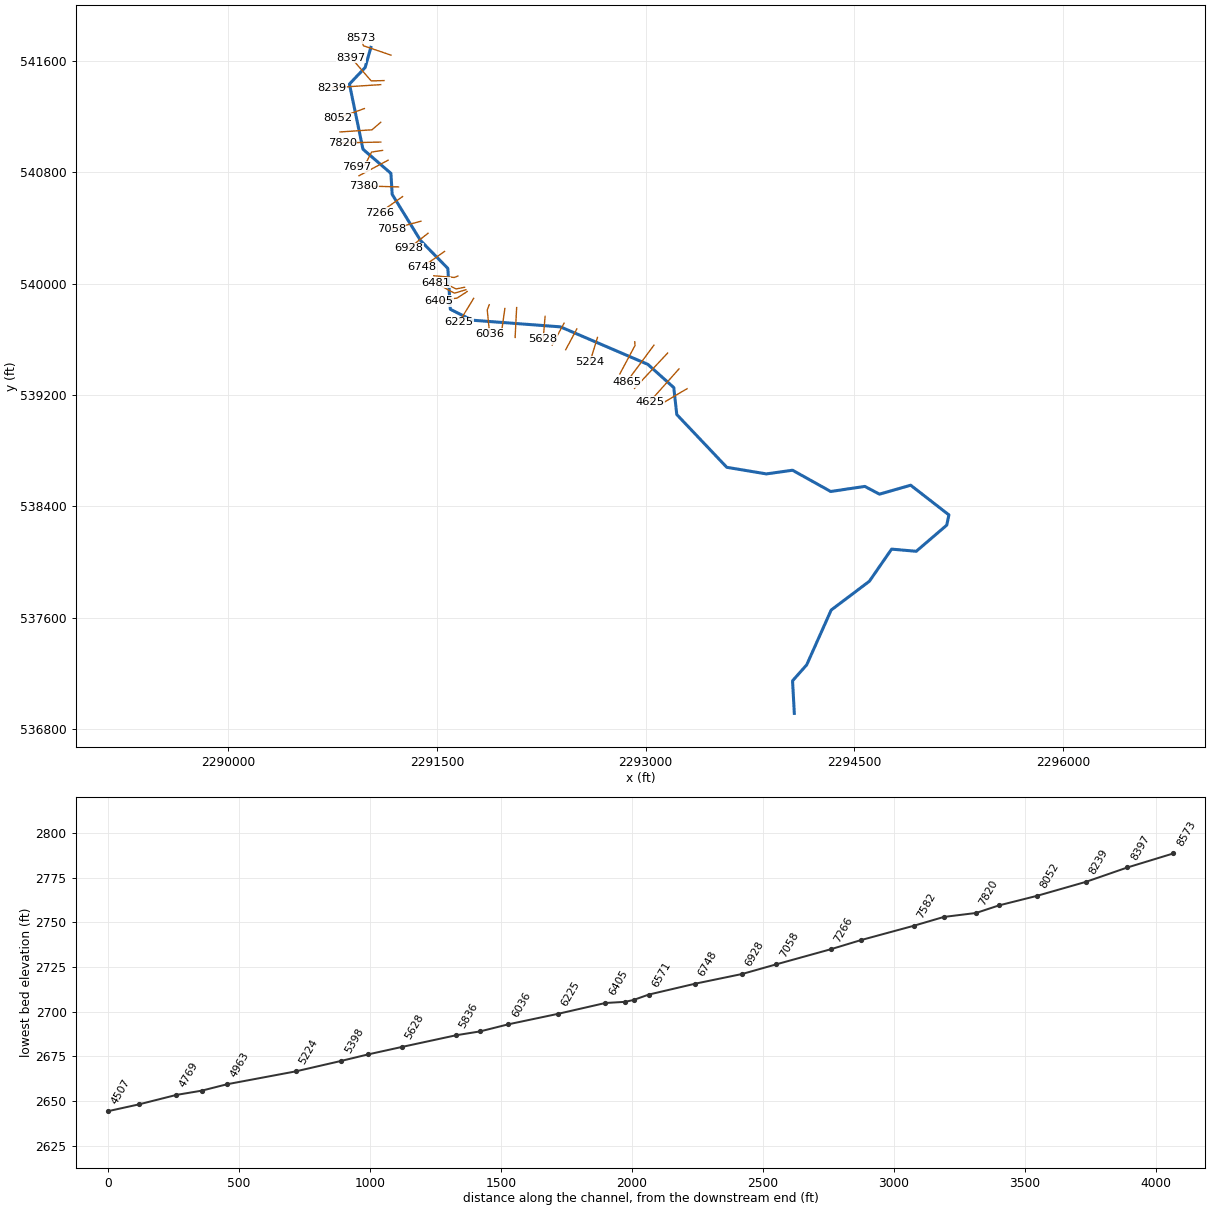
--- ALGHNYRN.prj (project) ---

Proj Title=ALGHNYRN
Current Plan=p01
Default Exp/Contr=0,0
English Units
Geom File=g01
Flow File=f01
Plan File=p01
BEGIN DESCRIPTION:
----------MODEL BY WOOD PLC 2021----------
Stream Name: Allegheny Run
Flood Zone: Enhanced Approximate
Pocahontas County, WV
HEC-RAS Version: RAS 6.1
Vertical Datum: NAVD88
Projection: NAD 1983 StatePlane West Virginia S FIPS 4702 (US Feet)
Terrain: 1-meter LIDAR (FEMA Region III 3DEP collected 2016-2018)
Land Use: 2019 NLCD
Hydrologic Method:
WV SIR2010-5033 regression equations
END DESCRIPTION:
DSS Export Rating Curves= 0
DSS Export Rating Curve Sorted= 0
DSS Export Volume Flow Curves= 0
DXF OffsetX= 0
DXF OffsetY= 0
DXF ScaleX= 0
DXF ScaleY= 0

--- ALGHNYRN.p01 (plan) ---

Plan Title=Floodplain
Program Version=6.10
Short Identifier=Floodplain
Geom File=g01
Flow File=f01
Subcritical Flow
K Sum by GR= 0
Std Step Tol= 0.01
Critical Tol= 0.01
Num of Std Step Trials= 20
Max Error Tol= 0.3
Flow Tol Ratio= 0.001
Split Flow NTrial= 30
Split Flow Tol= 0.02
Split Flow Ratio= 0.02
Log Output Level= 0
Friction Slope Method= 1
Unsteady Friction Slope Method= 2
Unsteady Bridges Friction Slope Method= 1
Parabolic Critical Depth
Global Vel Dist= 0 , 0 , 0
Global Log Level= 0
CheckData=True
Encroach Param=-1 ,0,0, 0
Mapping Interval=1HOUR
Computation Time Step Use Courant=        0
Computation Time Step Use Time Series=    0
Computation Time Step Count To Double=0
Computation Time Step Max Doubling=0
Computation Time Step Max Halving=0
Computation Time Step Residence Courant=0
Run HTab= 0
Run UNet= 0
Run Sediment= 0
Run PostProcess= 0
Run WQNet= 0
Run RASMapper= 0
UNET Theta= 0
UNET Theta Warmup= 0
UNET ZTol= 0
UNET ZSATol= 0
UNET MxIter= 0
UNET Max Iter WO Improvement= 0
UNET MaxInSteps= 0
UNET DtIC= 0
UNET DtMin= 0
UNET MaxCRTS= 0
UNET WFStab= 0
UNET SFStab= 0
UNET WFX= 1
UNET SFX= 1
UNET Gravity=32.174
UNET 1D Methodology=Finite Difference
UNET DSS MLevel= 1
UNET Pardiso=0
UNET DZMax Abort= 0
UNET Use Existing IB Tables= 0
UNET Froude Reduction=False
UNET Froude Limit= 0
UNET Froude Power= 0
UNET D1 Cores= 0
UNET WindReference=Eulerian
UNET WindDragFormulation=Hsu (1988)
UNET D2 Coriolis=0
UNET D2 Cores= 0
UNET D2 Theta= 1
UNET D2 Theta Warmup= 1
UNET D2 Z Tol= 0.01
UNET D2 Volume Tol= 0.01
UNET D2 Max Iterations= 20
UNET D2 Equation= 0
UNET D2 RampUpFraction=0.1
UNET D2 TimeSlices= 1
UNET D2 Turbulence Formulation=Non-Conservative (original)
UNET D2 Eddy Viscosity=0.3
UNET D2 Transverse Eddy Viscosity=0.1
UNET D2 Smagorinsky Mixing=0
UNET D2 BCVolumeCheck=0
UNET D2 Cores=0
UNET D2 SolverType=PARDISO (Direct)
UNET D2 Minimum Iterations= 2147483647
UNET D2 Maximum Iterations= 2147483647
UNET D2 Restart Number= 10
UNET D2 Relaxation Coeff=1.3
UNET D2 SOR Precondition Iterations= 10
UNET D2 ILUT Maximum Fill= 8
UNET D2 ILUT Tolerance=1E-08
UNET D1D2 MaxIter= 0
UNET D1D2 ZTol=0.01
UNET D1D2 QTol=0.1
UNET D1D2 MinQTol=1
Write IC File= 0
Write IC File at Fixed DateTime=0
Write IC File at Sim End=0
Echo Input=False
Echo Parameters=False
Echo Output=False
Write Detailed= 0
HDF Write Warmup=0
HDF Write Time Slices=0
HDF Flush=0
HDF Compression= 1
HDF Chunk Size= 1
HDF Spatial Parts= 1
HDF Use Max Rows=0
HDF Fixed Rows= 1
Calibration Method= 0
Calibration Iterations= 20
Calibration Max Change=0.05
Calibration Tolerance=0.2
Calibration Maximum=1.5
Calibration Minimum=0.5
Calibration Optimization Method= 1
WQ AD Non Conservative
WQ ULTIMATE=-1
WQ Max Comp Step=1HOUR
WQ Output Interval=15MIN
WQ Output Selected Increments= 0
WQ Output face flow=0
WQ Output face velocity=0
WQ Output face area=0
WQ Output face dispersion=0
WQ Output cell volume=0
WQ Output cell surface area=0
WQ Output cell continuity=0
WQ Output cumulative cell continuity=0
WQ Output face conc=0
WQ Output face dconc_dx=0
WQ Output face courant=0
WQ Output face peclet=0
WQ Output face adv mass=0
WQ Output face disp mass=0
WQ Output cell mass=0
WQ Output cell source sink temp=0
WQ Output nsm pathways=0
WQ Output nsm derived pathways=0
WQ Create Restart=0
WQ Fixed Restart=0
WQ System Summary=0
WQ Write To DSS=0
Sorting and Armoring Iterations= 10
XS Update Threshold= 0.02
Bed Roughness Predictor= 0
Hydraulics Update Threshold= 0.02
Energy Slope Method= 1
Volume Change Method= 1
Sediment Retention Method= 0
Sediment TS Multiplier= 1
Warm Up Method= 0
XS Weighting Method= 0
Number of US Weighted Cross Sections= 1
Number of DS Weighted Cross Sections= 1
Upstream XS Weight=0
Main XS Weight=1
Downstream XS Weight=0
Number of DS XS's Weighted with US Boundary= 1
Upstream Boundary Weight= 1
Weight of XSs Associated with US Boundary= 0
Number of US XS's Weighted with DS Boundary= 1
Downstream Boundary Weight= 0.5
Weight of XSs Associated with DS Boundary= 0.5
Percentile Method= 0
Sediment Output Level= 3
Mass or Volume Output= 0
Output Increment Type= 1
Profile and TS Output Increment= 1
Transport Output Increment 1
XS Output Flag= 0
XS Output Increment= 10
Read HDF5 Sediment Hotstart= 0
Sediment Hotstart Type= 0
Write Gradation File= 0
Read Gradation Hotstart= 0
Write HDF5 File= 1
Write Binary Output= 1
Write DSS Sediment File= 0
DSS Sediment Output Type= 1
SV Curve= 0
Specific Gage Flag= 0
Subcell Erosion Methods= 0
Subcell Deposition Methods= 0
Advection Scheme= 1
Matrix Solver= 0
Implicit Weighting Factor= 1
Maximum Outer Loop Convergence Iterations= 5
Convergence Maximum Absolute= 0.001
Convergence RMSE= 0.0001
Grain Fractions Max Abs Error= 0.001
Max Subgrid Regions= 1
Max Subgrid Length Scale= 3.402823E+38
Initial Layer Thickness= 3.402823E+38
Min Layer Thickness= 3.402823E+38
Max Layer Thickness= 3.402823E+38
Number of Layers= 5

--- ALGHNYRN.f01 (steady flow) ---

Flow Title=Flow
Program Version=6.10
Number of Profiles= 6
Profile Names=01pct,10pct,04pct,02pct,0_2pct,01plus
River Rch & RM=ALGHNYRN,Main,8573
     758     405     536     644    1050    1120
River Rch & RM=ALGHNYRN,Main,5928
     844     453     597     717    1170    1250
Boundary for River Rch & Prof#=ALGHNYRN,Main            , 1
Up Type= 0
Dn Type= 3
Dn Slope=0.02517
Boundary for River Rch & Prof#=ALGHNYRN,Main            , 2
Up Type= 0
Dn Type= 3
Dn Slope=0.02517
Boundary for River Rch & Prof#=ALGHNYRN,Main            , 3
Up Type= 0
Dn Type= 3
Dn Slope=0.02517
Boundary for River Rch & Prof#=ALGHNYRN,Main            , 4
Up Type= 0
Dn Type= 3
Dn Slope=0.02517
Boundary for River Rch & Prof#=ALGHNYRN,Main            , 5
Up Type= 0
Dn Type= 3
Dn Slope=0.02517
Boundary for River Rch & Prof#=ALGHNYRN,Main            , 6
Up Type= 0
Dn Type= 3
Dn Slope=0.02517
DSS Import GetInterval= 0
DSS Import GetPeak= 0
DSS Import FillOption= 0

--- ALGHNYRN.g01 (geometry) ---

Geom Title=Geometry
Program Version=6.10

River Reach=ALGHNYRN        ,Main
Reach XY= 30
     2291024.603      541699.187     2290983.336      541554.515
     2290870.537      541435.723     2290967.644      540967.366
       2291168.5      540793.964     2291177.712      540642.666
     2291382.105      540310.239     2291577.786      540110.544
     2291595.506      539817.103     2291751.356      539738.547
     2292387.326       539690.43     2293015.449      539420.856
     2293201.762      539254.198     2293223.267      539060.193
      2293582.71      538680.935     2293866.911      538633.661
     2294055.361      538660.001     2294329.447      538507.158
      2294574.91      538543.717     2294680.033      538488.045
     2294904.523      538552.271     2295179.062      538338.951
     2295163.641      538265.328     2294944.434      538077.401
     2294767.225      538093.026     2294607.539      537862.146
     2294332.924       537655.01     2294157.014      537261.254
     2294055.318      537146.508     2294068.071      536912.431

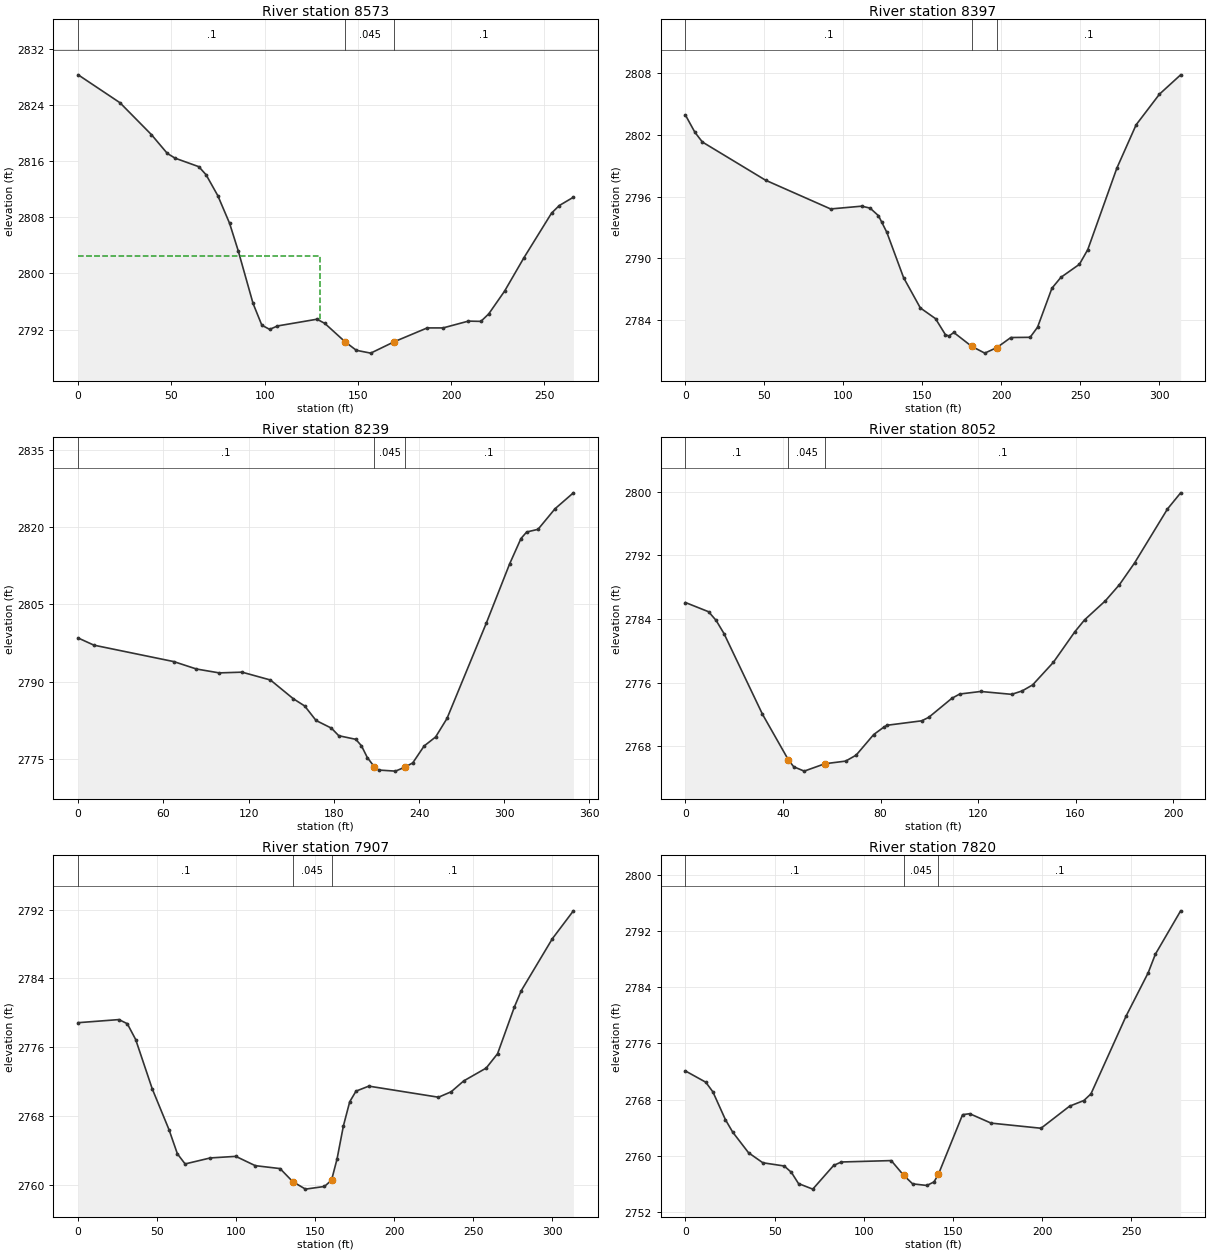
Type RM Length L Ch R = 1 ,8573    ,183.5,176,169.2
XS GIS Cut Line= 3
2291169.42661938541643.4069542482290971.28029949541710.766710946
2290953.77297702541764.243361247
#Sta/Elev= 30
       0 2828.27    22.4  2824.3    39.3 2819.75    47.8 2817.08      52  2816.4
    64.7 2815.19    68.6 2814.04    74.9 2811.06    81.2 2807.13    85.8 2803.25
    93.8 2795.71    98.5 2792.62   102.7 2792.02   106.9 2792.51   128.1 2793.47
   132.3 2792.87   143.12790.267   149.2 2789.04   156.9 2788.64   169.5 2790.26
   187.2 2792.23   195.7 2792.23   209.3  2793.2     216 2793.16   220.2 2794.23
   228.7 2797.47     239 2802.19   253.9 2808.58     258 2809.65   265.6 2810.84
#Mann= 3 ,-1,0
       0      .1       0   143.1    .045       0   169.5      .1       0
#XS Ineff= 2 , 0
          129.57 2802.52
Permanent Ineff=
       F       F
Bank Sta=143.1,169.5
XS Rating Curve= 0 ,0
Exp/Cntr(USF)=0,0
Exp/Cntr=0.3,0.1

Type RM Length L Ch R = 1 ,8397    ,144.2,157.7,167.1
XS GIS Cut Line= 3
2291118.85304651541460.6605646022291026.96497585541458.304460226
2290881.67187268541625.587870908
#Sta/Elev= 30
       0 2803.93       6 2802.25    10.7 2801.31    50.7 2797.59    91.9 2794.79
   111.6 2795.06   116.9 2794.87   122.2 2794.13   124.3 2793.49   127.5 2792.51
   138.1  2788.1   148.7 2785.15   158.3 2784.11   164.6 2782.54   166.8 2782.42
   169.9 2782.76   181.2 2781.41   189.5 2780.75   197.22781.295     206 2782.27
   218.2 2782.29   222.9 2783.27     232 2787.07   237.7 2788.13   249.4  2789.4
   254.7 2790.83   273.1 2798.76   285.3 2802.98   300.1 2805.97   313.5 2807.85
#Mann= 3 ,-1,0
       0      .1       0   181.2    .045       0   197.2      .1       0
Bank Sta=181.2,197.2
XS Rating Curve= 0 ,0
Exp/Cntr(USF)=0,0
Exp/Cntr=0.3,0.1

Type RM Length L Ch R = 1 ,8239    ,182.7,187.1,189.8
XS GIS Cut Line= 2
2291095.29200275541431.6019439672290747.37392326541408.826268334
#Sta/Elev= 30
       0 2798.51    11.1 2797.12    67.3 2793.94    83.3  2792.5    99.3 2791.75
   115.4 2791.89   135.4 2790.37   151.4 2786.76   159.5 2785.34   167.5 2782.53
   178.3 2781.05   183.5 2779.58   195.5 2778.88   199.5 2777.62   203.6 2775.35
   208.4 2773.61   211.6 2772.93   223.4 2772.72   230.12773.491   235.6 2774.32
   243.6 2777.59   251.7 2779.34   259.7 2782.92   287.4  2801.4   303.8 2812.86
   311.8 2817.78   315.8 2819.04   323.8 2819.56   335.8 2823.55   348.7 2826.63
#Mann= 3 ,-1,0
       0      .1       0   208.4    .045       0   230.1      .1       0
Bank Sta=208.4,230.1
XS Rating Curve= 0 ,0
Exp/Cntr(USF)=0,0
Exp/Cntr=0.3,0.1

Type RM Length L Ch R = 1 ,8052    ,150.1,145.6,142.8
XS GIS Cut Line= 2
2290977.89753111541259.6646109242290787.10275981541189.973107633
#Sta/Elev= 30
       0 2786.07     9.5 2784.91    12.6 2783.81    15.8 2782.17    31.6 2772.01
    42.2 2766.29    44.4 2765.41    48.7 2764.86    57.2 2765.79    65.7 2766.12
      70 2766.87    77.2 2769.46    81.3 2770.38    82.7 2770.63    96.9 2771.19
    99.8 2771.63   109.3 2774.03   112.5 2774.56   121.1 2774.88   133.8 2774.52
   138.1 2774.95   142.4 2775.71   150.9 2778.55   159.7 2782.39   163.7 2783.89
   172.2 2786.28     178 2788.32   184.2 2791.05   197.7 2797.84   203.1 2799.87
#Mann= 3 ,-1,0
       0      .1       0    42.2    .045       0    57.2      .1       0
Bank Sta=42.2,57.2
XS Rating Curve= 0 ,0
Exp/Cntr(USF)=0,0
Exp/Cntr=0.3,0.1

Type RM Length L Ch R = 1 ,7907    ,87.3,86.6,86.1
XS GIS Cut Line= 3
2291095.74426541541161.1228454392291032.72089733541106.825789865
2290802.92800142541091.312345415
#Sta/Elev= 30
       0 2778.85    25.8 2779.21    31.1 2778.73    36.4 2776.89    46.9 2771.15
    57.5 2766.41    62.8  2763.6    67.7 2762.42    83.7 2763.12    99.8  2763.3
   112.1 2762.22   127.8 2761.88   135.9 2760.35   143.9 2759.49   155.9  2759.8
   160.4 2760.53   163.9 2763.01   167.9 2766.84   171.9 2769.65   175.9 2770.89
     184 2771.47   228.1 2770.18   236.1 2770.81   244.1 2772.08   258.3 2773.57
   265.5 2775.24   276.2  2780.7   280.5 2782.57   300.2 2788.62   313.5 2791.86
#Mann= 3 ,-1,0
       0      .1       0   135.9    .045       0   160.4      .1       0
Bank Sta=135.9,160.4
XS Rating Curve= 0 ,0
Exp/Cntr(USF)=0,0
Exp/Cntr=0.3,0.1

Type RM Length L Ch R = 1 ,7820    ,103.1,123.4,139
XS GIS Cut Line= 2
2291095.57334814541018.6005585572290817.94981864541012.888140255
#Sta/Elev= 30
       0 2772.09    11.4 2770.49    15.4 2769.11    22.4 2765.17    26.5 2763.39
    35.4 2760.45    43.4 2759.03    55.4 2758.57    59.4 2757.67    63.4 2756.07
    71.4 2755.28    83.1 2758.65    87.4 2759.14   115.4 2759.34   122.3 2757.27
   127.4 2756.03   135.4  2755.8   139.4 2756.31   141.9 2757.42   155.4 2765.87
   159.4 2766.01   171.4 2764.67   199.4 2763.94   215.4 2767.08   223.4 2767.88
   227.4 2768.83   247.1  2779.9   259.5 2786.06   263.5 2788.69   277.7 2794.87
#Mann= 3 ,-1,0
       0      .1       0   122.3    .045       0   141.9      .1       0
Bank Sta=122.3,141.9
XS Rating Curve= 0 ,0
Exp/Cntr(USF)=0,0
Exp/Cntr=0.3,0.1

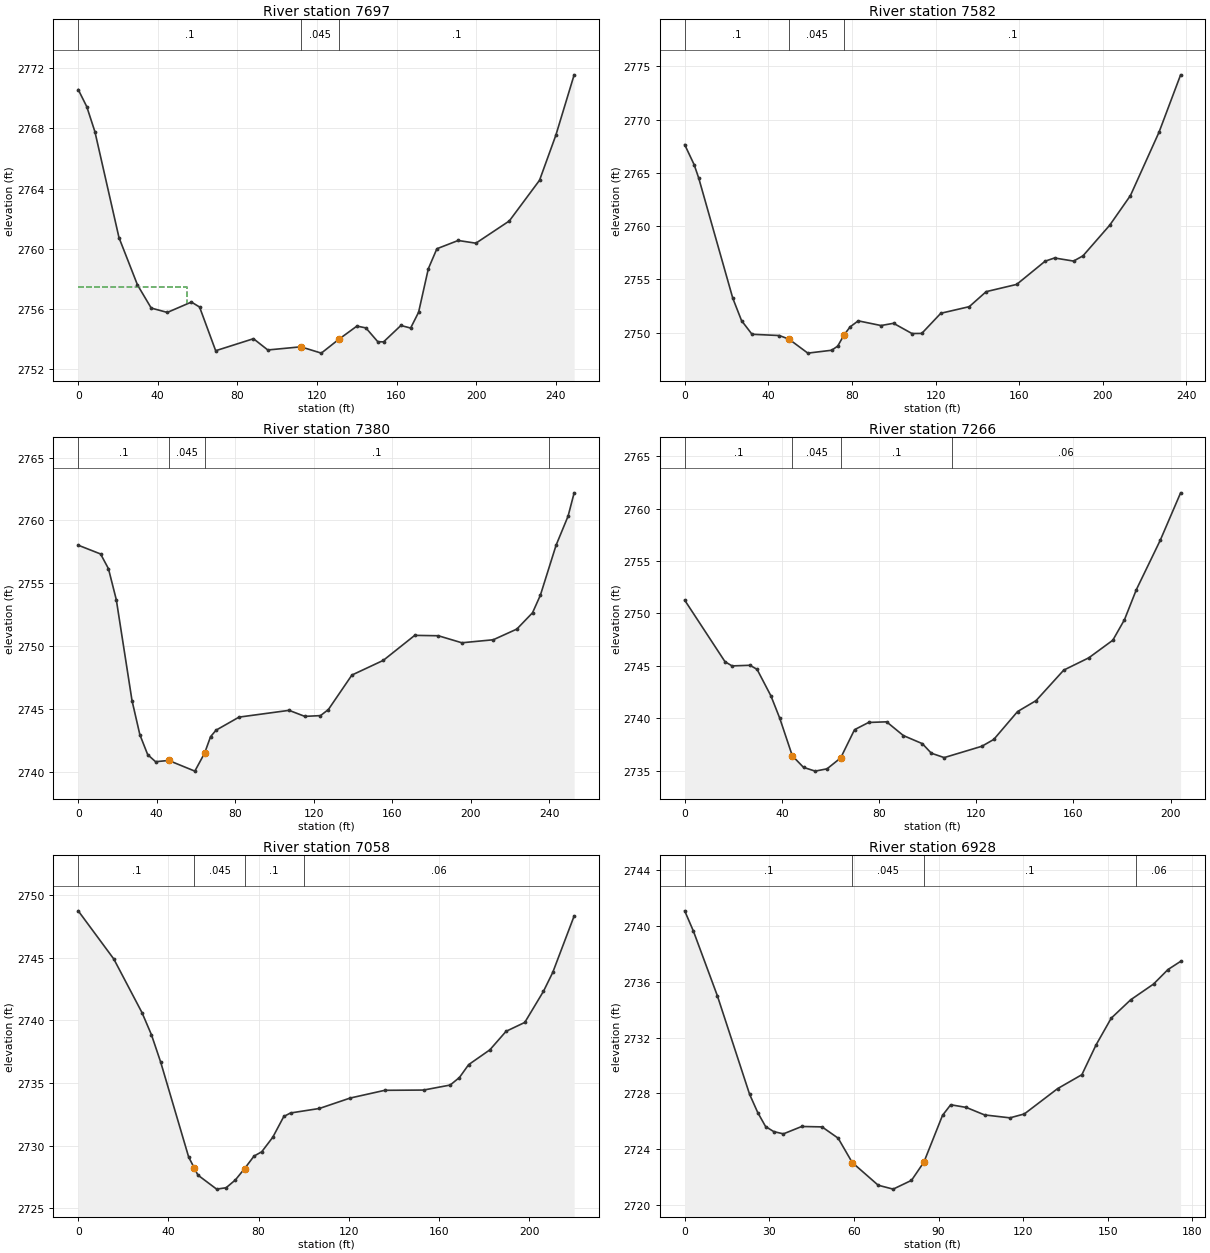
Type RM Length L Ch R = 1 ,7697    ,124.9,115,105.6
XS GIS Cut Line= 4
 2291108.4751539540958.7983519412291029.45088315540946.870160129
 2290981.7381159 540852.935649612290919.11510888540839.516433821
#Sta/Elev= 30
       0 2770.59     4.3 2769.45     8.4 2767.78    20.5 2760.73    29.8 2757.58
    36.7 2756.04    44.8 2755.75    56.9 2756.44      61 2756.11    69.1  2753.2
    88.1    2754    95.3 2753.25   111.9 2753.46   122.2 2753.04   131.2 2753.98
   140.1 2754.84   144.6 2754.72   150.6  2753.8   153.5 2753.79   162.2 2754.88
   167.1 2754.71   171.1 2755.76     176 2758.66   180.3 2759.99     191 2760.54
   199.9 2760.36   216.7 2761.84   231.9 2764.55   240.1 2767.55   249.3 2771.57
#Mann= 3 ,-1,0
       0      .1       0   111.9    .045       0   131.2      .1       0
#XS Ineff= 2 , 0
           54.92 2757.45
Permanent Ineff=
       F       F
Bank Sta=111.9,131.2
XS Rating Curve= 0 ,0
Exp/Cntr(USF)=0,0
Exp/Cntr=0.3,0.1

Type RM Length L Ch R = 1 ,7582    ,208.7,201.9,194.7
XS GIS Cut Line= 2
2291148.12759653 540888.357421262290939.05308665540776.394022531
#Sta/Elev= 30
       0 2767.65     4.5 2765.78     6.7 2764.52      23 2753.24    27.2 2751.13
    32.2 2749.85    45.3 2749.73    49.9 2749.39    58.9 2748.08    70.3 2748.35
    73.2 2748.74    76.2 2749.78    79.1 2750.54      83 2751.11    93.9 2750.67
    99.9 2750.88   108.7 2749.92   113.4 2749.93   122.5 2751.82   136.1 2752.44
   144.2 2753.85   158.8 2754.53   172.4 2756.71   176.9 2757.01     186 2756.72
   190.5 2757.21   203.3 2760.09   213.2 2762.87   226.9 2768.83   237.2  2774.2
#Mann= 3 ,-1,0
       0      .1       0    49.9    .045       0    76.2      .1       0
Bank Sta=49.9,76.2
XS Rating Curve= 0 ,0
Exp/Cntr(USF)=0,0
Exp/Cntr=0.3,0.1

Type RM Length L Ch R = 1 ,7380    ,103.9,113.9,122.4
XS GIS Cut Line= 2
2291223.53151812540696.4201662952290971.04262915540703.275068259
#Sta/Elev= 30
       0 2758.03    11.4 2757.33    15.4 2756.16    19.4 2753.69    27.4 2745.66
    31.4 2742.94    35.4 2741.35    39.4 2740.79    46.1 2740.89    59.4 2740.04
    64.4 2741.48    67.4 2742.78    70.2  2743.3    81.9 2744.34   107.4 2744.88
   115.4  2744.4   123.4 2744.46   127.4 2744.94   139.4 2747.69   155.4 2748.86
   171.4 2750.85   183.4 2750.82   195.4 2750.26   211.4  2750.5   223.4 2751.35
   231.4 2752.65   235.4 2754.05   243.4 2758.03   249.5 2760.34   252.6  2762.2
#Mann= 4 ,-1,0
       0      .1       0    46.1    .045       0    64.4      .1       0
     240     .06       0
Bank Sta=46.1,64.4
XS Rating Curve= 0 ,0
Exp/Cntr(USF)=0,0
Exp/Cntr=0.3,0.1

Type RM Length L Ch R = 1 ,7266    ,213,207.8,201.8
XS GIS Cut Line= 2
2291252.09360963540626.728663005 2291085.2909952540509.052845973
#Sta/Elev= 30
       0 2751.27    16.6  2745.4    19.5    2745    26.9 2745.06    29.8 2744.67
    35.5 2742.14    39.1 2740.03    44.3 2736.43    48.9 2735.33    53.7 2734.97
    58.6 2735.19    64.2 2736.23    69.9 2738.92    75.7 2739.61    83.1 2739.67
      90 2738.36    97.8 2737.59   101.5 2736.68   106.8 2736.26   122.3 2737.34
   127.2 2737.99     137 2740.65   144.6 2741.69     156  2744.6   166.3 2745.77
   176.2 2747.45     181 2749.41   185.9 2752.28   195.7 2756.97   204.1  2761.5
#Mann= 4 ,-1,0
       0      .1       0    44.3    .045       0    64.2      .1       0
     110     .06       0
Bank Sta=44.3,64.2
XS Rating Curve= 0 ,0
Exp/Cntr(USF)=0,0
Exp/Cntr=0.3,0.1

Type RM Length L Ch R = 1 ,7058    ,122.6,130.3,136.2
XS GIS Cut Line= 2
2291383.47923059540449.6436956272291170.97726974540392.519512601
#Sta/Elev= 30
       0 2748.74    15.8 2744.89    28.3 2740.61    32.5 2738.84    36.6 2736.65
      49 2729.08    51.52728.202    53.1 2727.64    61.4 2726.52    65.6 2726.63
    69.7 2727.25    73.8 2728.16      78 2729.16    81.4  2729.5    86.3 2730.66
    91.2 2732.32    94.2  2732.6     107 2732.96   120.6 2733.79     136 2734.41
   153.2 2734.43     165 2734.83   169.1 2735.43   173.2 2736.46   182.6 2737.64
   189.8 2739.12   198.1 2739.83   206.4 2742.32   210.5 2743.82     220 2748.33
#Mann= 4 ,-1,0
       0      .1       0    51.5    .045       0    73.8      .1       0
     100     .06       0
Bank Sta=51.5,73.8
XS Rating Curve= 0 ,0
Exp/Cntr(USF)=0,0
Exp/Cntr=0.3,0.1

Type RM Length L Ch R = 1 ,6928    ,178.6,179.6,177.9
XS GIS Cut Line= 2
2291434.89099531540362.8149374282291296.65047239 540254.27898968
#Sta/Elev= 30
       0  2741.1     3.1 2739.64    11.6 2734.99      23 2727.93    25.9 2726.61
    28.7  2725.6    31.6 2725.24      35 2725.08    41.5 2725.61    48.7 2725.58
    54.4 2724.77    59.4 2723.02    68.6 2721.39    73.9 2721.11    80.4 2721.74
    84.8 2723.05    91.4 2726.41    94.3 2727.17    99.8 2726.98   106.3 2726.44
   115.3 2726.23   120.4 2726.51   132.2 2728.33   140.8 2729.33   145.8 2731.46
   151.2 2733.39   158.1 2734.71   166.2 2735.84   171.3 2736.88   175.8 2737.47
#Mann= 4 ,-1,0
       0      .1       0    59.4    .045       0    84.8      .1       0
     160     .06       0
Bank Sta=59.4,84.8
XS Rating Curve= 0 ,0
Exp/Cntr(USF)=0,0
Exp/Cntr=0.3,0.1

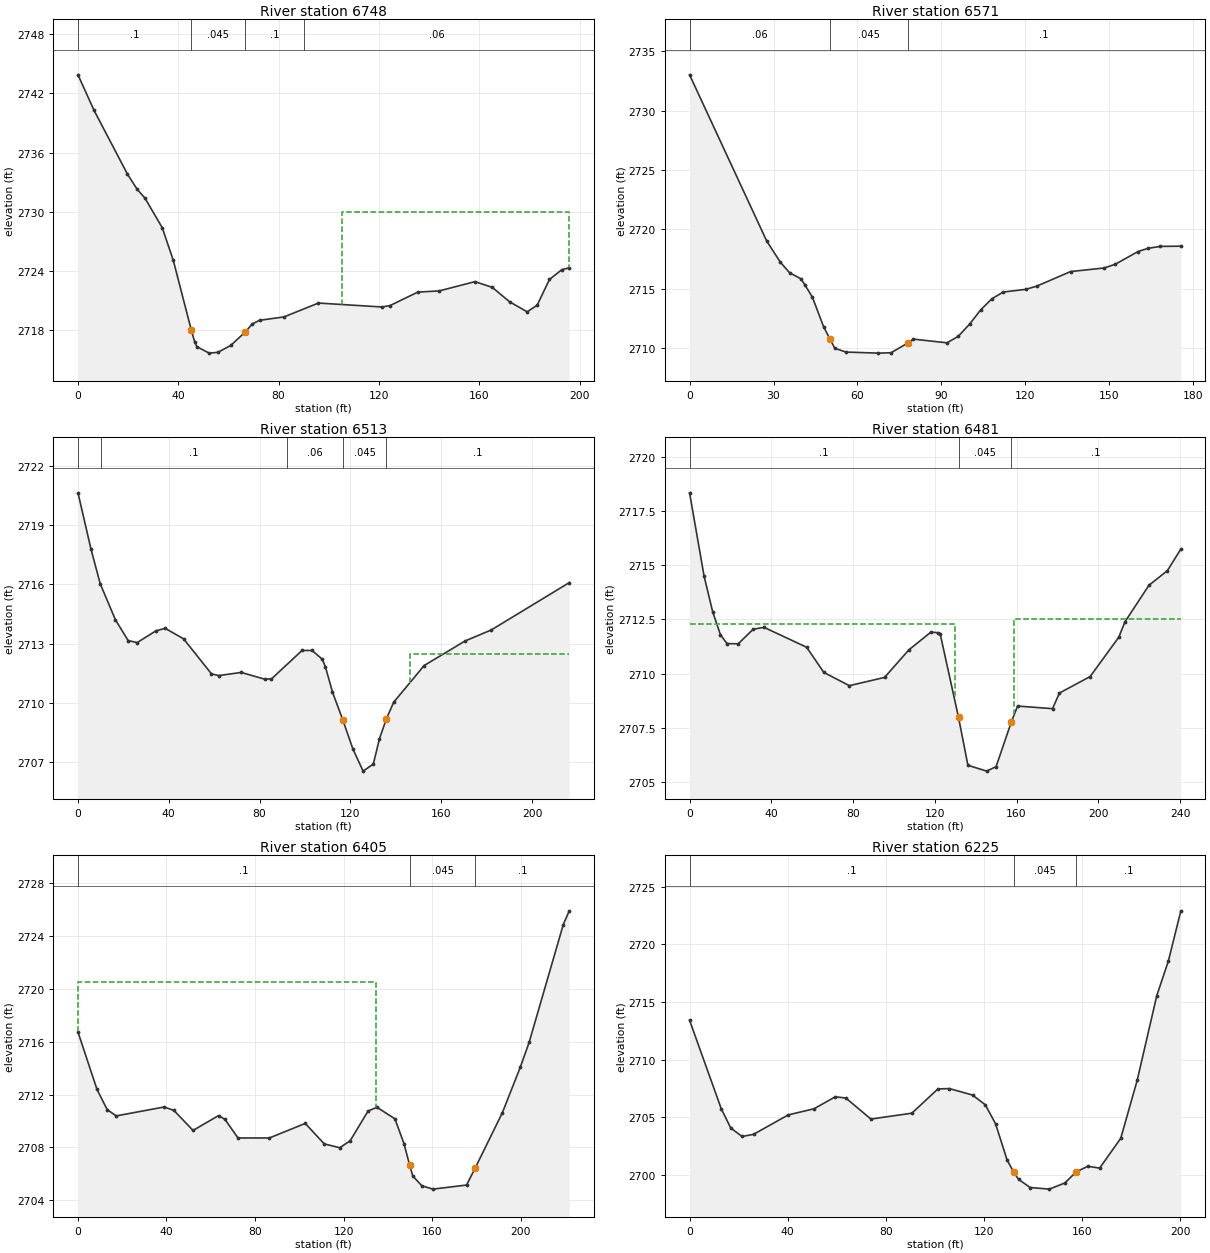
Type RM Length L Ch R = 1 ,6748    ,191.3,177.1,165.5
XS GIS Cut Line= 2
  2291553.709296540232.5718001312291393.76158353540119.465917741
#Sta/Elev= 30
       0 2743.89     6.4 2740.29    19.7 2733.83    23.6 2732.28    26.7 2731.39
    33.6 2728.38      38 2725.08    45.22717.982    46.6 2716.75    47.4 2716.32
    52.3 2715.66    55.8 2715.74    60.9 2716.44    66.7  2717.8    69.5 2718.62
    72.4 2718.99    82.1 2719.33    95.9 2720.74   121.2 2720.34   124.4 2720.48
   135.5 2721.85     144 2721.97   158.3 2722.91   165.2 2722.33   172.1 2720.87
   179.1 2719.85   183.1 2720.52     188 2723.13   192.9 2724.12   195.9 2724.32
#Mann= 4 ,-1,0
       0      .1       0    45.2    .045       0    66.7      .1       0
      90     .06       0
#XS Ineff= 2 , 0
                          105.31         2729.99
Permanent Ineff=
       F       F
Bank Sta=45.2,66.7
XS Rating Curve= 0 ,0
Exp/Cntr(USF)=0,0
Exp/Cntr=0.3,0.1

Type RM Length L Ch R = 1 ,6571    ,63.8,57.8,51.9
XS GIS Cut Line= 3
 2291649.9688721540055.785198023 2291624.3951809540045.457361193
2291476.85465476540057.752405038
#Sta/Elev= 30
       0 2733.03    27.6    2719    32.5 2717.21    35.8 2716.33    39.8 2715.83
    41.3 2715.29    43.9 2714.28    47.9 2711.79    50.12710.789    51.9 2709.97
    55.9 2709.65    67.5 2709.56      72 2709.59    77.92710.398      80 2710.74
      92 2710.43      96 2710.97   100.1 2712.01   104.1 2713.22   108.1 2714.15
   112.1 2714.71   120.2 2714.94   124.1 2715.21   136.2 2716.44   148.2 2716.74
   152.2 2717.06   160.3 2718.13   163.9  2718.4   168.2 2718.56   175.6 2718.58
#Mann= 3 ,-1,0
       0     .06       0    50.1    .045       0    77.9      .1       0
Bank Sta=50.1,77.9
XS Rating Curve= 0 ,0
Exp/Cntr(USF)=0,0
Exp/Cntr=0.5,0.3

Type RM Length L Ch R = 1 ,6513    ,33.9,31.8,30.8
XS GIS Cut Line= 4
 2291697.8058825539974.9911717042291637.03938345539962.926813638
2291602.78219071539979.984944236 2291499.3247888540032.745695491
#Sta/Elev= 30
       0 2720.63     5.7  2717.8     9.8 2716.03    16.5 2714.21    22.1 2713.16
    26.1 2713.06    34.3 2713.65    38.4 2713.78    46.5 2713.25    58.8 2711.48
      62 2711.39    71.9 2711.55    82.2 2711.21    85.2 2711.22    98.7 2712.66
   103.1 2712.66   107.6 2712.22     109 2711.83   112.1 2710.56   116.6 2709.16
   121.1 2707.68   125.6 2706.56   130.1 2706.92   132.8  2708.2   135.8 2709.19
   139.1 2710.05   152.5  2711.9   170.5 2713.14   182.1  2713.7   216.4 2716.09
#Mann= 5 ,-1,0
       0     .06       0      10      .1       0   91.95     .06       0
   116.6    .045       0   135.8      .1       0
#XS Ineff= 2 , 0
          104.11 2712.52  146.14          2712.5
Permanent Ineff=
       F       F
Bank Sta=116.6,135.8
XS Rating Curve= 0 ,0
Exp/Cntr(USF)=0,0
Exp/Cntr=0.5,0.3

Type RM Length L Ch R = 1 ,6481    ,63.4,76.1,88
XS GIS Cut Line= 5
2291706.96952957539957.2478271152291626.33996308539932.503410701
2291587.60907118539951.9572484052291530.14100057539984.439201357
2291490.16321232540008.592448424
#Sta/Elev= 30
       0 2718.33     7.1 2714.49    11.3 2712.85    15.1 2711.79    18.3 2711.38
    23.8 2711.37    31.1 2712.04    36.4 2712.13    57.3 2711.21    65.7 2710.05
    78.2 2709.44    95.4 2709.82   107.3 2711.09   118.1 2711.91   121.5 2711.88
   122.6 2711.84   131.6 2707.98   136.2 2705.77   145.4  2705.5     150 2705.71
   157.5 2707.78   160.5  2708.5   177.6 2708.38     181  2709.1     196 2709.86
     210 2711.67   213.1 2712.39   224.8 2714.07   233.8 2714.74   240.4 2715.74
#Mann= 3 ,-1,0
       0      .1       0   131.6    .045       0   157.5      .1       0
#XS Ineff= 2 , 0
          129.71  2712.3   158.7          2712.5
Permanent Ineff=
       F       F
Bank Sta=131.6,157.5
XS Rating Curve= 0 ,0
Exp/Cntr(USF)=0,0
Exp/Cntr=0.5,0.3

Type RM Length L Ch R = 1 ,6405    ,162.7,180.1,196.6
XS GIS Cut Line= 3
2291716.85882863539944.3625926812291644.58307591539897.514448149
2291510.29717401539876.769359637
#Sta/Elev= 30
       0 2716.73     8.6 2712.39    13.2 2710.86    17.3 2710.39    38.9 2711.06
    43.3 2710.81      52 2709.29    63.5 2710.41    66.4 2710.13    72.3 2708.72
    86.5 2708.72   102.7 2709.82   111.3 2708.27   118.3 2707.98     123 2708.51
   131.1 2710.76   135.1 2711.04   143.2 2710.17   147.3  2708.3   149.9 2706.65
   151.3 2705.84   155.4  2705.1   160.4 2704.85   175.6 2705.16   179.6 2706.48
   191.8 2710.64   199.9 2714.08   203.9 2715.97   219.3 2724.86     222  2725.9
#Mann= 3 ,-1,0
       0      .1       0   149.9    .045       0   179.6      .1       0
#XS Ineff= 2 , 0
          134.54 2720.53
Permanent Ineff=
       F       F
Bank Sta=149.9,179.6
XS Rating Curve= 0 ,0
Exp/Cntr(USF)=0,0
Exp/Cntr=0.3,0.1

Type RM Length L Ch R = 1 ,6225    ,177.7,189.6,200.5
XS GIS Cut Line= 2
2291763.57507723539895.4578262822291658.82130366 539724.80261771
#Sta/Elev= 30
       0 2713.42    12.9 2705.76    16.8 2704.08    21.4 2703.35    26.1 2703.54
    40.2 2705.22    50.7 2705.75    59.4 2706.79    63.7 2706.68    73.9 2704.86
    90.6 2705.37   101.2 2707.47   105.9  2707.5   115.3 2706.94   120.5  2706.1
   124.7 2704.45   129.4 2701.31   132.1 2700.26   134.1 2699.63   138.8 2698.93
   146.6 2698.79   152.9 2699.32   157.6 2700.29   162.3 2700.77   167.1 2700.61
   175.7 2703.19   182.4 2708.21   190.4 2715.56   195.1 2718.54   200.2  2722.9
#Mann= 3 ,-1,0
       0      .1       0   132.1    .045       0   157.6      .1       0
Bank Sta=132.1,157.6
XS Rating Curve= 0 ,0
Exp/Cntr(USF)=0,0
Exp/Cntr=0.3,0.1

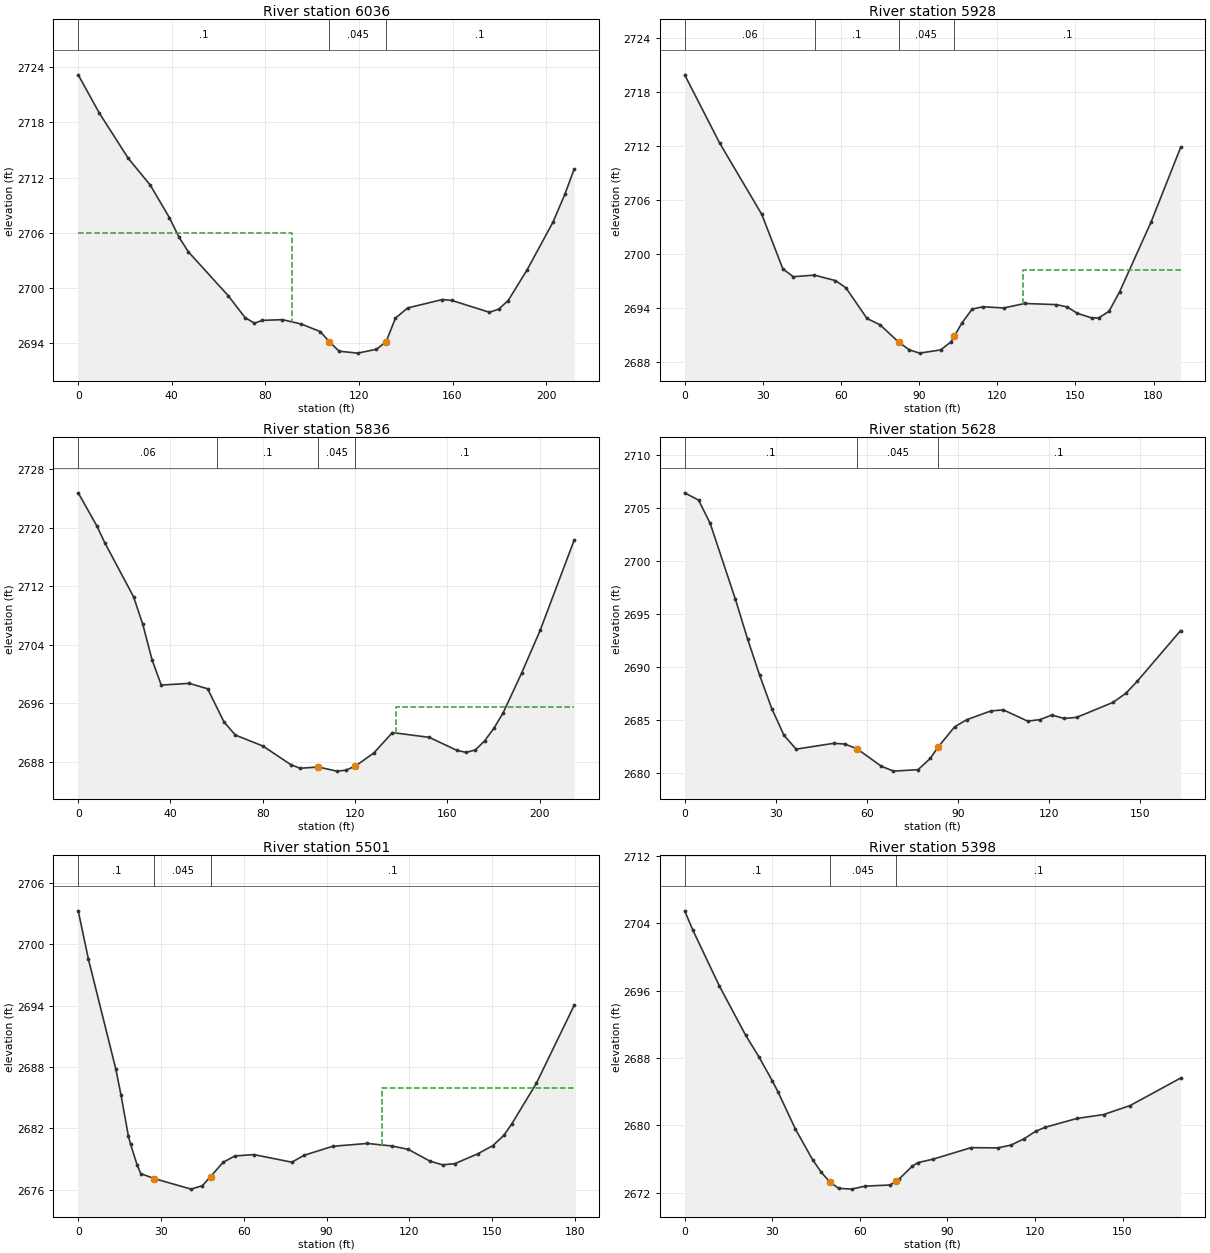
Type RM Length L Ch R = 1 ,6036    ,110.3,107.1,102.2
XS GIS Cut Line= 3
2291875.21407534539849.7202631772291860.95182448 539811.35972638
2291878.16488586539641.196319563
#Sta/Elev= 30
       0 2723.18       9 2719.03    21.4  2714.1    30.8 2711.19      39 2707.64
    43.1 2705.52    47.1 2703.93    64.1 2699.17    71.3 2696.79    75.3 2696.18
    78.7 2696.48    87.3 2696.56    95.4 2696.08   103.4 2695.27   107.4 2694.16
   111.5 2693.13   119.5 2692.92   127.5 2693.34   131.6 2694.15   135.6 2696.72
   140.8 2697.83   155.7 2698.75   159.7 2698.65   175.8 2697.36   179.8 2697.71
   183.8 2698.64   191.9 2701.98   202.9 2707.14     208 2710.17     212 2712.93
#Mann= 3 ,-1,0
       0      .1       0   107.4    .045       0   131.6      .1       0
#XS Ineff= 2 , 0
            91.3 2705.97
Permanent Ineff=
       F       F
Bank Sta=107.4,131.6
XS Rating Curve= 0 ,0
Exp/Cntr(USF)=0,0
Exp/Cntr=0.3,0.1

Type RM Length L Ch R = 1 ,5928    ,92,92.8,94.3
XS GIS Cut Line= 2
2291987.72633996539822.469823747 2291960.6747712539633.981473682
#Sta/Elev= 30
       0  2719.9    13.4 2712.33    29.6 2704.39    37.7 2698.33    41.7 2697.46
    49.8 2697.64    57.9 2697.03    61.9 2696.23      70 2692.82      75 2692.12
    82.1 2690.21    86.2 2689.34    90.2 2688.97    98.3 2689.33   102.3 2690.24
   103.52690.832   106.4 2692.31   110.4 2693.87   114.5 2694.12   122.5 2693.99
   130.6 2694.49   142.7 2694.36   146.8 2694.11   150.8 2693.39   156.2 2692.89
   158.9 2692.88   162.9 2693.61     167  2695.8   179.1 2703.57   190.4 2711.83
#Mann= 4 ,-1,0
       0     .06       0      50      .1       0    82.1    .045       0
   103.5      .1       0
#XS Ineff= 2 , 0
                          129.84         2698.25
Permanent Ineff=
       F       F
Bank Sta=82.1,103.5
XS Rating Curve= 0 ,0
Exp/Cntr(USF)=0,0
Exp/Cntr=0.3,0.1

Type RM Length L Ch R = 1 ,5836    ,207,207.5,206.7
XS GIS Cut Line= 2
 2292072.2626447539829.1738787962292061.33371684  539614.4204463
#Sta/Elev= 30
       0 2724.75       8 2720.28    11.5 2717.95      24 2710.56      28  2706.8
      32 2701.98      36 2698.51    48.1 2698.75    56.1 2698.01    63.2 2693.48
    68.1  2691.7    80.1 2690.19    92.1 2687.67    96.1 2687.16   104.1 2687.33
   112.1 2686.77   116.1  2686.9   120.2 2687.47   128.2 2689.26   136.2 2692.03
   152.2 2691.38   164.2  2689.6   168.2 2689.33   172.2 2689.67   176.2 2690.91
   180.2 2692.61   184.2 2694.72   192.2 2700.13   200.3 2706.01     215 2718.29
#Mann= 4 ,-1,0
       0     .06       0      60      .1       0   104.1    .045       0
   120.2      .1       0
#XS Ineff= 2 , 0
                           137.7         2695.48
Permanent Ineff=
       F       F
Bank Sta=104.1,120.2
XS Rating Curve= 0 ,0
Exp/Cntr(USF)=0,0
Exp/Cntr=0.3,0.1

Type RM Length L Ch R = 1 ,5628    ,132.1,127.3,119.6
XS GIS Cut Line= 2
2292276.63359573539765.786097194 2292262.9724359539602.945072045
#Sta/Elev= 30
       0 2706.41     4.6 2705.72     8.4 2703.53    16.7  2696.4    20.7 2692.67
    24.7 2689.23    28.7 2686.09    32.7 2683.59    36.7 2682.27    49.1 2682.82
    52.8 2682.75    56.8  2682.3    64.8 2680.66    68.8  2680.2    76.9 2680.34
    80.9 2681.39    83.4 2682.43    88.9 2684.36    92.9 2685.04   100.9 2685.87
     105 2685.97     113 2684.91     117 2685.05     121 2685.48     125 2685.16
   129.1 2685.26   141.1 2686.67   145.4 2687.54   149.1 2688.66   163.4 2693.44
#Mann= 3 ,-1,0
       0      .1       0    56.8    .045       0    83.4      .1       0
Bank Sta=56.8,83.4
XS Rating Curve= 0 ,0
Exp/Cntr(USF)=0,0
Exp/Cntr=0.3,0.1

Type RM Length L Ch R = 1 ,5501    ,101.9,102.7,102.4
XS GIS Cut Line= 2
2292413.24519401539717.1523682072292327.45311029539559.229360595
#Sta/Elev= 30
       0 2703.25     3.7 2698.53    13.6 2687.83    15.5 2685.28    18.2 2681.23
      19 2680.45    21.4 2678.39    22.7 2677.59    27.62677.107    40.9 2676.08
      45 2676.42      48 2677.31    52.5  2678.7    56.8 2679.32    63.7 2679.45
    77.4 2678.71    81.9 2679.39    92.2 2680.26   104.7 2680.54   113.8 2680.29
   119.6 2679.96   127.4 2678.82     132 2678.45   136.5 2678.57   144.7 2679.52
   150.2 2680.32   154.2 2681.32   157.1 2682.45     166 2686.41   179.7 2694.02
#Mann= 3 ,-1,0
       0      .1       0    27.6    .045       0      48      .1       0
#XS Ineff= 2 , 0
                          109.98            2686
Permanent Ineff=
       F       F
Bank Sta=27.6,48
XS Rating Curve= 0 ,0
Exp/Cntr(USF)=0,0
Exp/Cntr=0.3,0.1

Type RM Length L Ch R = 1 ,5398    ,170,173.6,176.4
XS GIS Cut Line= 2
2292505.04818805539675.6224423292292424.72056826539525.896130615
#Sta/Elev= 30
       0  2705.5     2.8 2703.21    11.9 2696.56    20.9 2690.71    25.5 2688.11
      30 2685.31      32 2683.97    37.9 2679.59    43.8 2675.94    46.8 2674.43
    49.7 2673.29    52.7 2672.53    57.2 2672.43    61.8 2672.79    70.4 2672.92
    72.4 2673.39    73.4 2673.61      78 2675.17    79.9 2675.58    85.2    2676
    98.1 2677.36   107.2 2677.33   111.8 2677.66   116.3 2678.42   120.3 2679.32
   123.6 2679.79   134.4 2680.83   143.5 2681.29   152.6 2682.36   169.9 2685.63
#Mann= 3 ,-1,0
       0      .1       0    49.7    .045       0    72.4      .1       0
Bank Sta=49.7,72.4
XS Rating Curve= 0 ,0
Exp/Cntr(USF)=0,0
Exp/Cntr=0.3,0.1

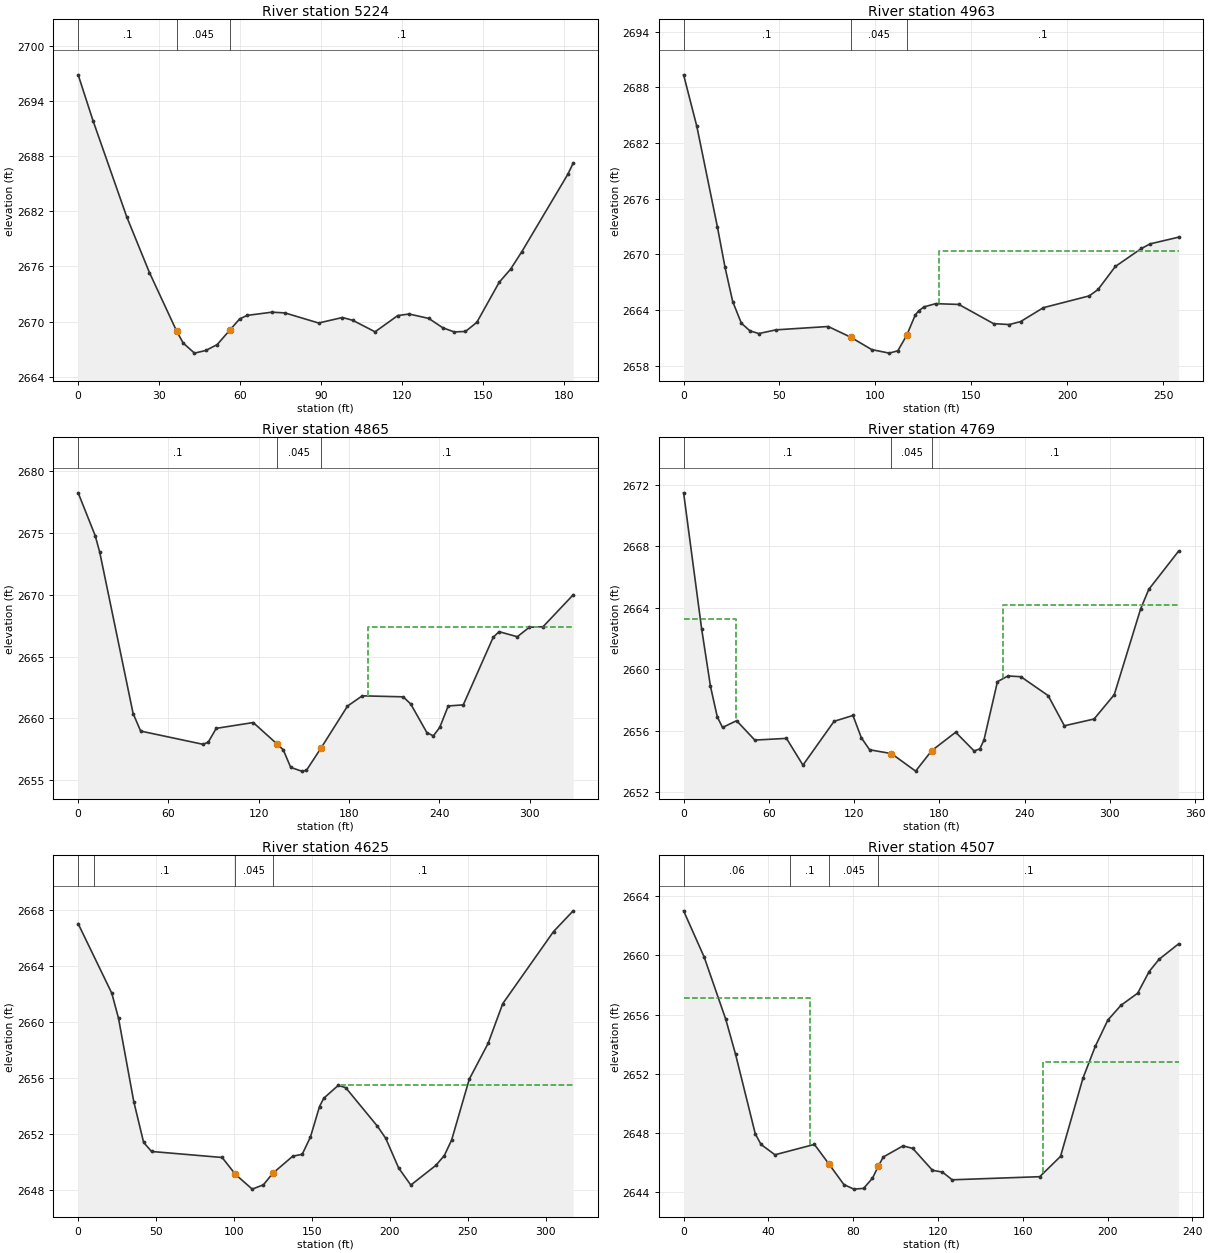
Type RM Length L Ch R = 1 ,5224    ,265.6,261.9,257.9
XS GIS Cut Line= 2
2292653.13516059  539614.42044632292599.58341406539439.011154108
#Sta/Elev= 30
       0 2696.87     5.5 2691.88      18  2681.4    26.4 2675.34    36.5 2668.95
    38.9 2667.66    43.1 2666.56    47.3 2666.85    51.5 2667.49    56.2 2669.07
    59.8 2670.28    62.6 2670.67    71.8 2671.02    76.6 2670.94    89.1 2669.84
    97.9 2670.44   101.7 2670.14     110 2668.88   118.4 2670.65   122.6 2670.82
   129.9 2670.34   135.1 2669.32   139.3 2668.87   143.5 2668.92   147.7 2669.91
     156 2674.28   160.2  2675.7   164.4 2677.62   181.4 2686.03   183.4 2687.25
#Mann= 3 ,-1,0
       0      .1       0    36.5    .045       0    56.2      .1       0
Bank Sta=36.5,56.2
XS Rating Curve= 0 ,0
Exp/Cntr(USF)=0,0
Exp/Cntr=0.3,0.1

Type RM Length L Ch R = 1 ,4963    ,100.2,97.3,94.4
XS GIS Cut Line= 3
2292920.89389321539582.7265554992292923.07967879539556.497128629
2292813.79040016539352.126177602
#Sta/Elev= 30
       0 2689.36     6.9  2683.8    17.6 2672.99    21.6 2668.61    25.6 2664.92
    30.1 2662.59    34.6 2661.76    39.2 2661.47    48.2 2661.87    75.4 2662.23
    87.1 2661.08    98.1 2659.74   107.2 2659.36   111.7 2659.61   116.3 2661.27
   120.8 2663.48   122.5  2663.9   125.3 2664.34   131.4 2664.69   143.5 2664.61
   161.6 2662.54   169.8 2662.44   175.7 2662.76   187.6 2664.26   211.5 2665.53
   216.1 2666.22   225.1  2668.7   238.7 2670.64   243.3 2671.14   258.1 2671.86
#Mann= 3 ,-1,0
       0      .1       0    87.1    .045       0   116.3      .1       0
#XS Ineff= 2 , 0
                          133.33         2670.34
Permanent Ineff=
       F       F
Bank Sta=87.1,116.3
XS Rating Curve= 0 ,0
Exp/Cntr(USF)=0,0
Exp/Cntr=0.3,0.1

Type RM Length L Ch R = 1 ,4865    ,98.5,96.7,94.3
XS GIS Cut Line= 2
2293058.88658632539558.5150303692292862.81388563539294.571010216
#Sta/Elev= 30
       0 2678.25    11.3 2674.79    14.3 2673.46    36.5  2660.4    41.5 2658.98
    82.9 2657.91    86.4 2658.08    91.7  2659.2   116.3 2659.67   132.32657.912
   136.2 2657.47   141.2 2656.04   148.4 2655.74   151.6  2655.8   161.52657.642
   178.9    2661   188.7 2661.83   215.9 2661.75   220.9 2661.17   231.6 2658.86
   235.9 2658.59   240.2 2659.28   245.8 2661.01   255.8  2661.1   275.7 2666.57
   279.6 2667.02   291.7 2666.61   299.7 2667.38   308.8 2667.42   328.8    2670
#Mann= 3 ,-1,0
       0      .1       0   132.3    .045       0   161.5      .1       0
#XS Ineff= 2 , 0
                          192.42         2667.43
Permanent Ineff=
       F       F
Bank Sta=132.3,161.5
XS Rating Curve= 0 ,0
Exp/Cntr(USF)=0,0
Exp/Cntr=0.3,0.1

Type RM Length L Ch R = 1 ,4769    ,142.1,143.9,143.9
XS GIS Cut Line= 2
2293157.64685272539502.4529057252292919.50416535539248.119214112
#Sta/Elev= 30
       0 2671.46    12.7 2662.61    18.9 2658.88    23.7 2656.89    27.4  2656.2
    37.3 2656.64    50.1 2655.38    72.4 2655.49      84 2653.75   105.9  2656.6
   119.2 2656.98   125.1 2655.53   130.9 2654.75   146.3  2654.5   163.3 2653.36
   174.6 2654.69   191.5 2655.89   204.5 2654.67   208.5 2654.81   211.4 2655.38
   220.9 2659.18   228.3 2659.55   237.4  2659.5   256.6 2658.27     268 2656.31
   288.9 2656.75   303.1 2658.33   321.7 2663.92   327.4 2665.18   348.4 2667.67
#Mann= 3 ,-1,0
       0      .1       0   146.3    .045       0   174.6      .1       0
#XS Ineff= 2 , 0
           36.86 2663.23  224.88         2664.14
Permanent Ineff=
       F       F
Bank Sta=146.3,174.6
XS Rating Curve= 0 ,0
Exp/Cntr(USF)=0,0
Exp/Cntr=0.3,0.1

Type RM Length L Ch R = 1 ,4625    ,123.9,117.9,113.5
XS GIS Cut Line= 2
2293239.32622331539388.4849827992293027.81756015539151.470629646
#Sta/Elev= 30
       0 2666.99    21.6 2662.02    25.9 2660.23    35.7 2654.28      42 2651.37
    47.1 2650.72    92.4 2650.29   100.9 2649.09   111.7 2648.03   118.9 2648.34
   124.9 2649.16   137.7 2650.38   143.8 2650.52   149.1 2651.76   154.9 2653.93
   157.6 2654.52   166.9 2655.44   171.7 2655.28   192.1 2652.52   197.4 2651.66
   205.7 2649.54   213.5 2648.32   229.6 2649.73     235 2650.43   239.7 2651.54
     251 2655.88   263.1 2658.44   272.5 2661.28   305.1 2666.43   317.7 2667.91
#Mann= 4 ,-1,0
       0     .06       0      10      .1       0   100.9    .045       0
   124.9      .1       0
#XS Ineff= 2 , 0
                          168.69         2655.44
Permanent Ineff=
       F       F
Bank Sta=100.9,124.9
XS Rating Curve= 0 ,0
Exp/Cntr(USF)=0,0
Exp/Cntr=0.3,0.1

Type RM Length L Ch R = 1 ,4507    ,213.8,217.5,217.8
XS GIS Cut Line= 2
 2293297.2942643539246.0953385822293096.25596164539127.361307484
#Sta/Elev= 30
       0 2663.01     9.7 2659.89    19.9 2655.68    24.5 2653.33    33.8 2647.96
    36.5 2647.24    43.1 2646.54    61.7 2647.24    68.7 2645.89    75.6 2644.53
    80.3 2644.22    84.9 2644.27    89.1 2644.96    91.82645.757    94.2 2646.39
   103.5 2647.14   108.1 2646.97   117.4 2645.49   122.1 2645.37   126.7 2644.85
     168 2645.06   177.8 2646.43   188.4 2651.72   194.2 2653.86   200.1 2655.63
   206.3 2656.63   214.2 2657.45   219.6 2658.91   224.3 2659.74   233.5 2660.78
#Mann= 4 ,-1,0
       0     .06       0      50      .1       0    68.7    .045       0
    91.8      .1       0
#XS Ineff= 2 , 0
           59.66 2657.11  169.67         2652.79
Permanent Ineff=
       F       F
Bank Sta=68.7,91.8
XS Rating Curve= 0 ,0
Exp/Cntr(USF)=0,0
Exp/Cntr=0.3,0.1