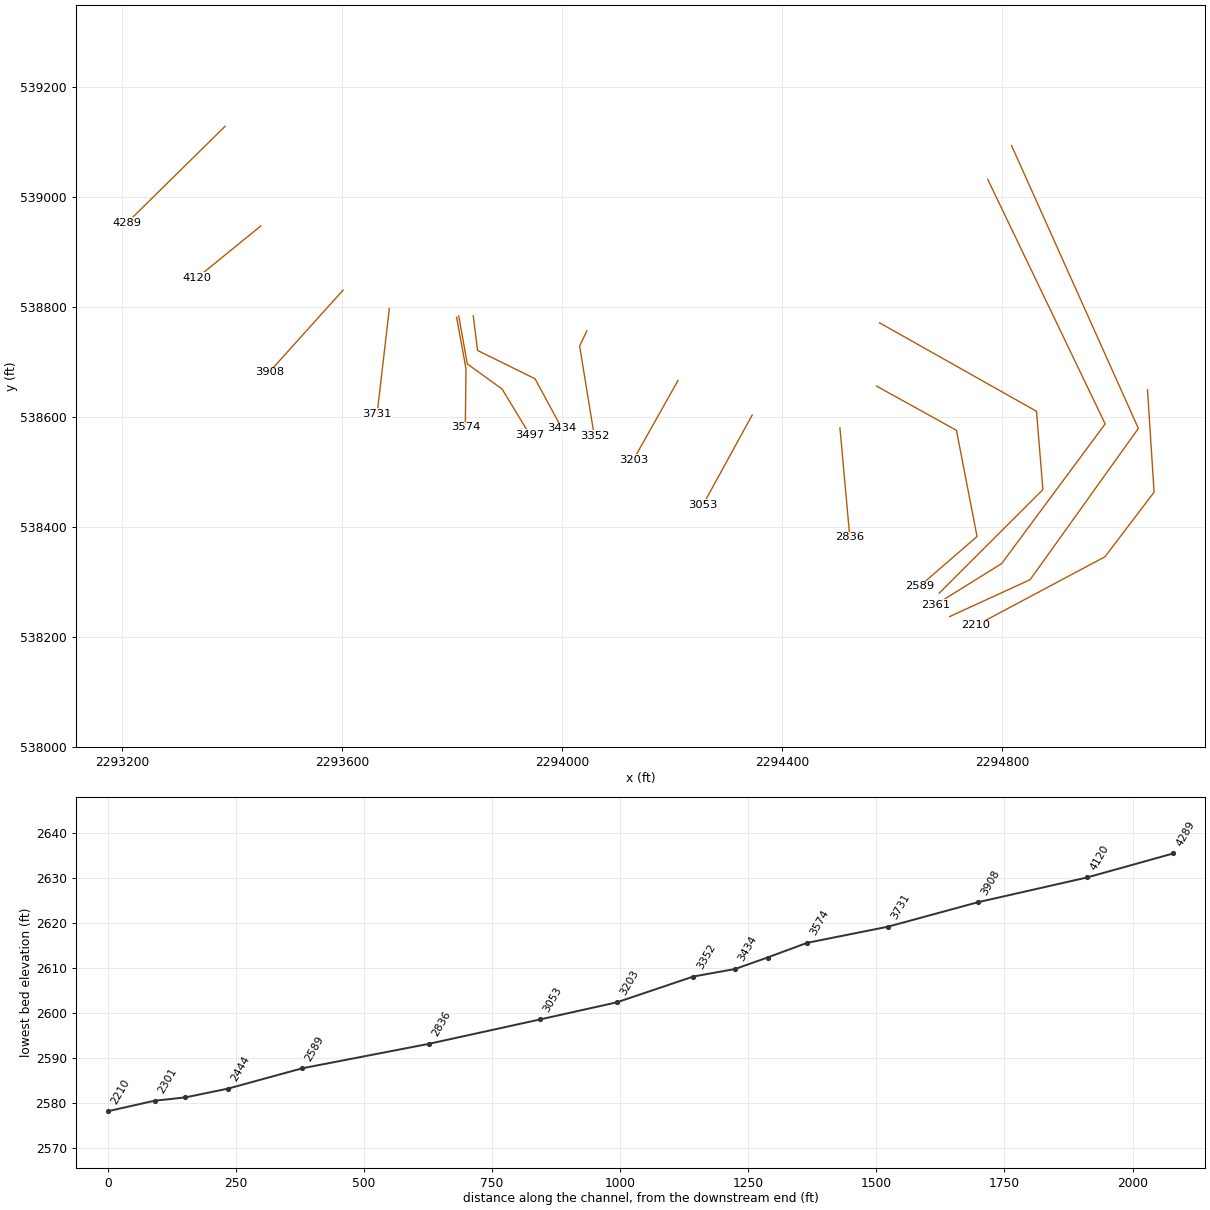
HEC-RAS study ALGHNYRN.prj: ALGHNYRN

--- ALGHNYRN.g01 (geometry) --- (continued)

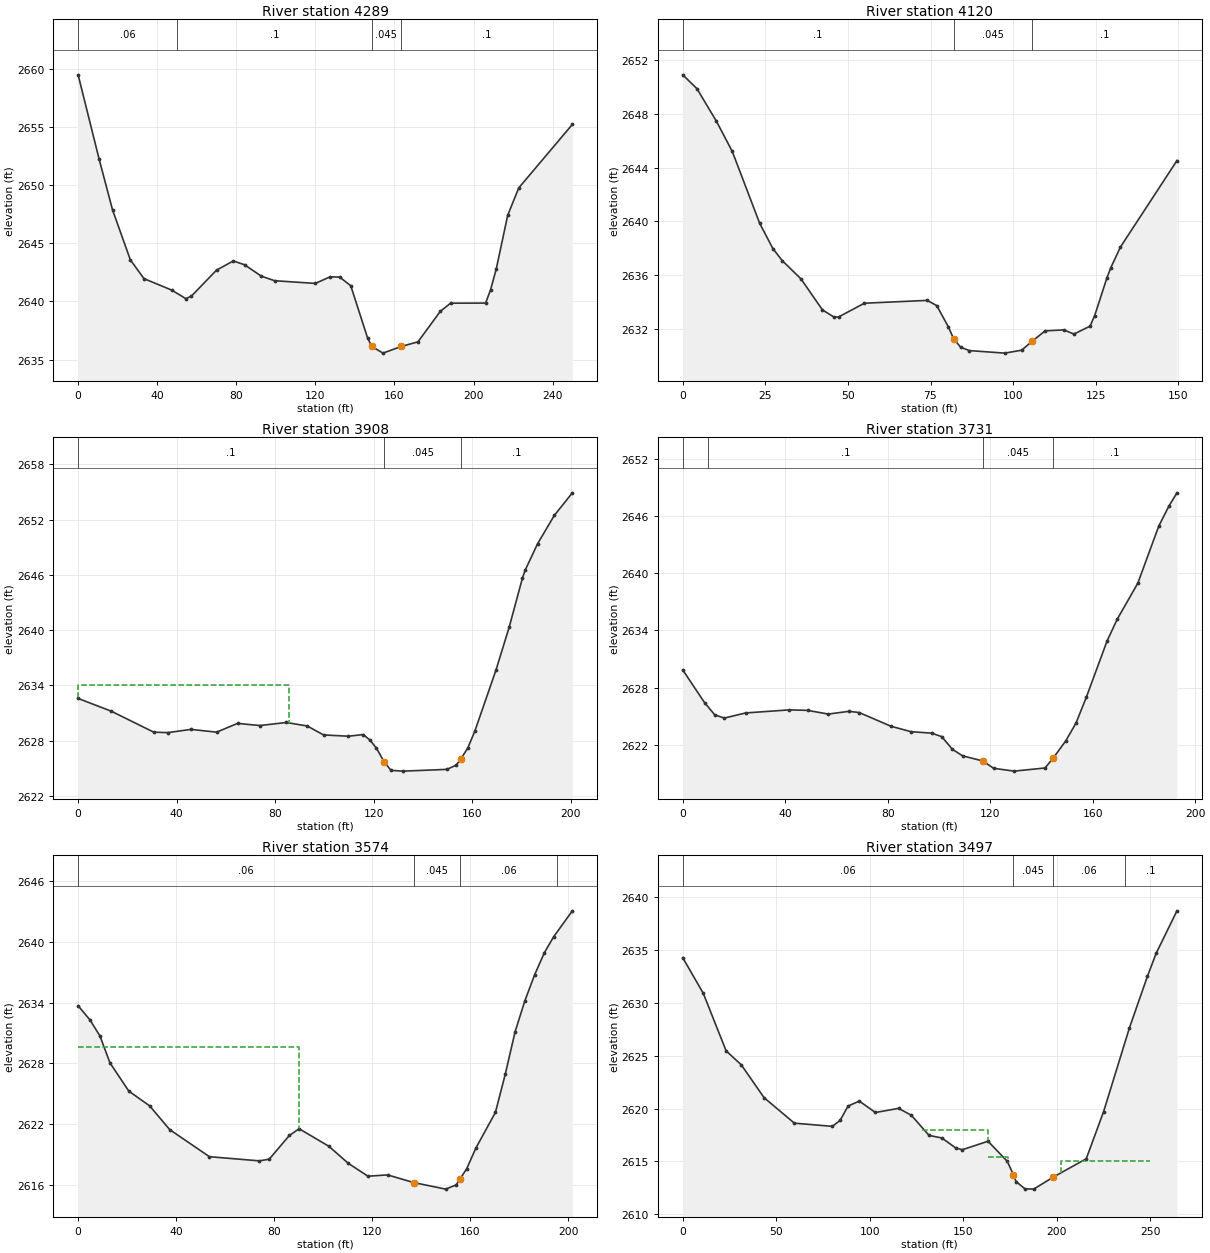
Type RM Length L Ch R = 1 ,4289    ,170.2,168.8,168.3
XS GIS Cut Line= 2
 2293387.0194128539129.3851830142293208.91836615538953.982637074
#Sta/Elev= 30
       0 2659.46    10.6 2652.23    17.4 2647.86    26.4 2643.57    33.3 2641.95
    47.4 2640.96    54.5 2640.23    57.3 2640.45      70 2642.68    78.5 2643.47
    84.2 2643.14    92.7 2642.16    99.4 2641.77     120 2641.54   127.5 2642.11
   132.3 2642.08   137.9 2641.34   146.4 2636.86   148.5 2636.13   154.2 2635.55
   163.4 2636.12   171.9 2636.52   183.2 2639.14   188.4 2639.84   206.1 2639.85
   208.6 2640.98   211.5 2642.78   217.3  2647.4   222.9 2649.75     250  2655.2
#Mann= 4 ,-1,0
       0     .06       0      50      .1       0   148.5    .045       0
   163.4      .1       0
Bank Sta=148.5,163.4
XS Rating Curve= 0 ,0
Exp/Cntr(USF)=0,0
Exp/Cntr=0.3,0.1

Type RM Length L Ch R = 1 ,4120    ,209.5,212.6,214.4
XS GIS Cut Line= 2
2293451.78342976538947.9110104842293335.74789937538853.463485747
#Sta/Elev= 30
       0 2650.93     4.3  2649.9    10.2 2647.47      15 2645.22    23.3 2639.86
    27.3 2637.98    30.1 2637.09    35.8 2635.72    42.3 2633.41    45.9 2632.86
    47.2 2632.89      55 2633.91      74 2634.12    76.9 2633.73    80.4 2632.15
      82 2631.26    84.1 2630.64    86.7 2630.38    97.5 2630.19   102.6 2630.41
   105.7 2631.06   109.7 2631.85   115.4 2631.92   118.4 2631.61   123.3  2632.2
   124.7 2632.99   128.4  2635.8   129.6 2636.57   132.5  2638.1   149.6 2644.54
#Mann= 3 ,-1,0
       0      .1       0      82    .045       0   105.7      .1       0
Bank Sta=82,105.7
XS Rating Curve= 0 ,0
Exp/Cntr(USF)=0,0
Exp/Cntr=0.3,0.1

Type RM Length L Ch R = 1 ,3908    ,166.4,176.5,190.8
XS GIS Cut Line= 2
2293601.55021899538831.2008549172293467.29980882538682.108690868
#Sta/Elev= 30
       0 2632.58    13.5 2631.19    30.7 2628.92    36.4 2628.87    45.8 2629.22
    56.2 2628.92    64.7 2629.87    73.8 2629.64    84.5 2629.97      93 2629.59
    99.6 2628.62   109.7 2628.48   115.7 2628.66   118.5 2628.05   121.1 2627.17
   124.2  2625.7     127 2624.77   131.9 2624.69   149.7 2624.88   153.4 2625.34
   155.3 2625.99   158.2 2627.23     161 2629.02   169.6 2635.66     175 2640.36
   180.3 2645.61   181.4 2646.48   186.5 2649.38   193.3 2652.46   200.6  2654.9
#Mann= 3 ,-1,0
       0      .1       0   124.2    .045       0   155.3      .1       0
#XS Ineff= 2 , 0
           85.39 2634.03
Permanent Ineff=
       F       F
Bank Sta=124.2,155.3
XS Rating Curve= 0 ,0
Exp/Cntr(USF)=0,0
Exp/Cntr=0.3,0.1

Type RM Length L Ch R = 1 ,3731    ,156.3,157.2,158.6
XS GIS Cut Line= 2
2293685.72994853538797.638252376 2293663.4673177538606.044702196
#Sta/Elev= 30
       0 2629.85     8.5 2626.42    12.5 2625.13    16.2 2624.79    24.6 2625.33
    41.5 2625.65    48.7  2625.6    56.8 2625.21    64.9  2625.5    68.9 2625.37
    81.2 2623.94    89.1 2623.36    97.1 2623.21   101.1 2622.84   105.2 2621.52
   109.2 2620.83   117.2 2620.28   121.3 2619.52   129.3 2619.22   141.4 2619.55
   144.6 2620.59   149.5  2622.4   153.5 2624.27   157.5 2626.96   165.6 2632.87
   169.6 2635.18   177.6 2638.94   185.8 2644.95   189.7 2647.02   192.9 2648.44
#Mann= 4 ,-1,0
       0     .06       0      10      .1       0   117.2    .045       0
   144.6      .1       0
Bank Sta=117.2,144.6
XS Rating Curve= 0 ,0
Exp/Cntr(USF)=0,0
Exp/Cntr=0.3,0.1

Type RM Length L Ch R = 1 ,3574    ,68.7,77.2,85.9
XS GIS Cut Line= 3
2293808.05395389538781.9319292352293825.21783509538687.997794258
2293823.88997036538581.768615435
#Sta/Elev= 30
       0 2633.68     4.8  2632.3     8.9 2630.71      13 2628.06    20.7 2625.28
    29.2 2623.83    37.4 2621.49    53.6 2618.83      74 2618.42      78 2618.59
    86.2 2620.92    90.2 2621.58   102.3 2619.86   110.3 2618.17   118.3 2616.91
   126.3 2617.04   136.92616.288     150 2615.64   154.3 2616.06   155.92616.652
   158.6 2617.66   162.3 2619.67   170.3 2623.19   174.3 2626.93   178.3  2631.1
   182.3 2634.16   186.3 2636.73   190.3 2638.91   194.1 2640.48   201.7 2643.02
#Mann= 4 ,-1,0
       0     .06       0   136.9    .045       0   155.9     .06       0
  195.49      .1       0
#XS Ineff= 2 , 0
            90.1 2629.64
Permanent Ineff=
       F       F
Bank Sta=136.9,155.9
XS Rating Curve= 0 ,0
Exp/Cntr(USF)=0,0
Exp/Cntr=0.5,0.3

Type RM Length L Ch R = 1 ,3497    ,62.5,63.3,62.6
XS GIS Cut Line= 4
2293812.03327411538783.9770925482293827.54965318538696.950444755
2293890.74097513538651.3573841642293941.54340285538567.677004475
#Sta/Elev= 30
       0 2634.28      11  2630.9    23.2 2625.46    31.3 2624.14    43.5 2621.03
    59.7 2618.62      80 2618.32    84.1 2618.88    88.4 2620.24    94.4 2620.71
     103 2619.63   115.4 2620.02   122.2 2619.37   131.7 2617.46   138.5 2617.22
     146 2616.27   149.5 2616.11   163.2 2616.91   173.5 2615.01   176.8 2613.73
   178.2  2613.1   182.9 2612.41   187.6 2612.38   198.1 2613.52   215.7 2615.25
     225 2619.72   238.8 2627.64   248.4 2632.51   253.1  2634.7   264.2 2638.71
#Mann= 4 ,-1,0
       0     .06       0   176.8    .045       0   198.1     .06       0
  236.32      .1       0
#XS Ineff= 3 ,-1
     128     163    2618     163     174  2615.4     202     250    2615
Permanent Ineff=
       F       F       F
Bank Sta=176.8,198.1
XS Rating Curve= 0 ,0
Exp/Cntr(USF)=0,0
Exp/Cntr=0.5,0.3

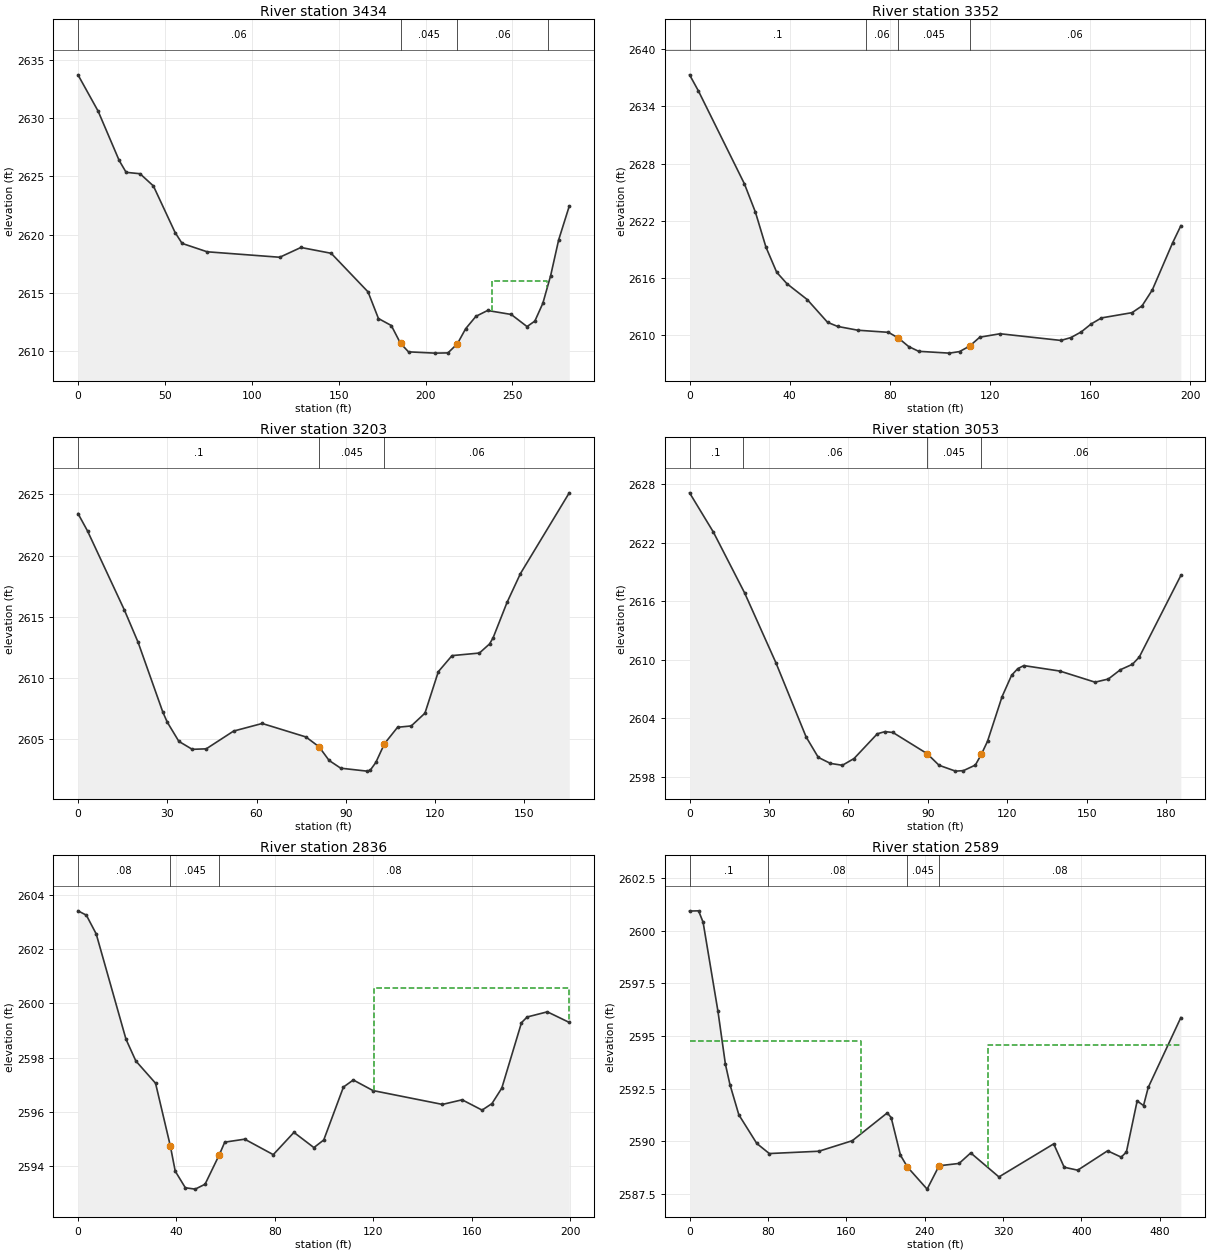
Type RM Length L Ch R = 1 ,3434    ,89.8,81.3,75.6
XS GIS Cut Line= 4
  2293838.343656538784.6517177252293846.25152384538721.455734388
2293950.81180433538669.9206747212293999.49527804538579.841929767
#Sta/Elev= 30
       0 2633.71    11.6 2630.59    23.7 2626.36    27.7 2625.34    35.7 2625.22
    43.4 2624.17    55.9 2620.17    59.9 2619.24    74.3 2618.52   116.1 2618.05
   128.3 2618.89   145.7 2618.39   166.9 2615.08   172.9 2612.79   180.3 2612.19
   185.6 2610.66   190.2 2609.93   205.4 2609.82   212.9 2609.84   218.3 2610.62
   223.1 2611.92     229 2612.98   235.7 2613.48   249.3 2613.14   258.4  2612.1
   262.9 2612.57   267.5  2614.1     272 2616.48   276.6 2619.54   282.7 2622.44
#Mann= 4 ,-1,0
       0     .06       0   185.6    .045       0   218.3     .06       0
  270.26      .1       0
#XS Ineff= 3 ,-1
     150     183  2611.4     222     238    2611     238     270    2616
Permanent Ineff=
       F       F       F
Bank Sta=185.6,218.3
XS Rating Curve= 0 ,0
Exp/Cntr(USF)=0,0
Exp/Cntr=0.5,0.3

Type RM Length L Ch R = 1 ,3352    ,163.6,149.6,137.6
XS GIS Cut Line= 3
2294045.05321905538756.9484001422294031.92779827538729.513817142
2294058.57776728538565.932598962
#Sta/Elev= 30
       0 2637.31     3.5 2635.64    21.9 2625.89    26.3 2622.92    30.5 2619.26
    34.8 2616.62    38.9 2615.42      47 2613.76    55.1 2611.38    59.1 2610.95
    67.2 2610.55    79.4 2610.33    83.4 2609.73    87.5 2608.84    91.5 2608.34
   103.7 2608.15   107.8 2608.31   111.8 2608.88   115.9 2609.82     124 2610.18
   148.3 2609.48   152.3 2609.78   156.4 2610.37   160.4 2611.21   164.5 2611.84
   176.7 2612.39   180.7  2613.1   184.8 2614.77   192.9  2619.7   196.2  2621.5
#Mann= 4 ,-1,0
       0      .1       0   70.41     .06       0    83.4    .045       0
   111.8     .06       0
Bank Sta=83.4,111.8
XS Rating Curve= 0 ,0
Exp/Cntr(USF)=0,0
Exp/Cntr=0.3,0.1

Type RM Length L Ch R = 1 ,3203    ,149.8,150.2,150.2
XS GIS Cut Line= 2
2294210.88011344538666.7654541012294129.92509224538522.845416406
#Sta/Elev= 30
       0 2623.43     3.2 2622.01    15.6 2615.55    20.2 2612.92    28.5 2607.23
      30  2606.4    33.9 2604.83    38.4 2604.18    43.1 2604.22    52.3 2605.67
    61.9 2606.29    76.6 2605.19      81 2604.39    84.4 2603.27    88.3 2602.64
    97.1  2602.4    98.2 2602.47   100.1 2603.11     103 2604.64   107.4 2605.98
     112 2606.09   116.6 2607.13   121.1 2610.52   125.7 2611.83   134.9 2612.04
   138.3 2612.78   139.5 2613.28   144.2 2616.18   148.7 2618.53   165.1 2625.12
#Mann= 3 ,-1,0
       0      .1       0      81    .045       0     103     .06       0
Bank Sta=81,103
XS Rating Curve= 0 ,0
Exp/Cntr(USF)=0,0
Exp/Cntr=0.3,0.1

Type RM Length L Ch R = 1 ,3053    ,207.8,216.7,225.7
XS GIS Cut Line= 2
2294345.80514878538603.8004376092294256.60470875538441.140811673
#Sta/Elev= 30
       0 2627.11       9 2623.08    20.8 2616.84    32.6 2609.69      44 2602.09
    48.6 2599.99    53.2 2599.37    57.7 2599.18    62.1 2599.87    70.9 2602.41
    73.8 2602.63    76.8 2602.54    89.7 2600.37    94.2 2599.18   100.4 2598.58
   103.4 2598.63   107.9  2599.2   110.22600.316   112.5 2601.64     118 2606.22
   121.6 2608.41   123.9 2609.08   126.2  2609.4   139.8 2608.84   153.1  2607.7
   158.1 2608.02   162.7 2608.98   167.2 2609.53   169.8 2610.27   185.5 2618.64
#Mann= 4 ,-1,0
       0      .1       0      20     .06       0    89.7    .045       0
   110.2     .06       0
Bank Sta=89.7,110.2
XS Rating Curve= 0 ,0
Exp/Cntr(USF)=0,0
Exp/Cntr=0.3,0.1

Type RM Length L Ch R = 1 ,2836    ,240,247,249.3
XS GIS Cut Line= 2
 2294505.4664406 538580.563348192294523.45644531 538381.92371283
#Sta/Elev= 30
       0 2603.41     3.4 2603.25     7.4 2602.56    19.5 2598.68    23.5 2597.88
    31.5 2597.06    37.52594.752    39.5 2593.82    43.6 2593.21    47.6 2593.16
    51.6 2593.34    57.42594.428    59.6 2594.89    67.7    2595    79.3 2594.43
    87.7 2595.25    95.8 2594.69    99.8 2594.97   107.8 2596.92   111.8 2597.18
   119.8 2596.79     148 2596.28     156 2596.45   164.1 2596.07   168.1 2596.31
   172.1 2596.88   180.1 2599.29   182.4  2599.5   190.6 2599.69   199.5  2599.3
#Mann= 3 ,-1,0
       0     .08       0    37.5    .045       0    57.4     .08       0
#XS Ineff= 2 , 0
                          120.19         2600.56
Permanent Ineff=
       F       F
Bank Sta=37.5,57.4
XS Rating Curve= 0 ,0
Exp/Cntr(USF)=0,0
Exp/Cntr=0.3,0.1

Type RM Length L Ch R = 1 ,2589    ,145.5,144.7,143.3
XS GIS Cut Line= 4
 2294572.1213127 538656.577945562294717.47231193538576.176178425
2294754.91192398538382.9394710772294650.12212481538292.217793555
#Sta/Elev= 30
       0 2600.93     9.2 2600.94    13.8  2600.4      29 2596.16    36.6 2593.65
    41.2 2592.69    50.3 2591.25    68.6 2589.89    81.4 2589.41     132 2589.52
   166.1 2590.02   201.8 2591.34   205.8 2591.12   215.3 2589.33   222.4 2588.77
   242.5 2587.72   254.7 2588.83   275.1 2588.94     287 2589.44   315.8  2588.3
   371.7 2589.87   382.4 2588.76   396.2 2588.62   426.7 2589.54   440.6 2589.24
   445.9 2589.48   456.9 2591.91   463.4 2591.69   468.2 2592.55   501.5 2595.87
#Mann= 4 ,-1,0
       0      .1       0      80     .08       0   222.4    .045       0
   254.7     .08       0
#XS Ineff= 2 , 0
          175.07 2594.76  304.35         2594.59
Permanent Ineff=
       F       F
Bank Sta=222.4,254.7
XS Rating Curve= 0 ,0
Exp/Cntr(USF)=0,0
Exp/Cntr=0.3,0.1

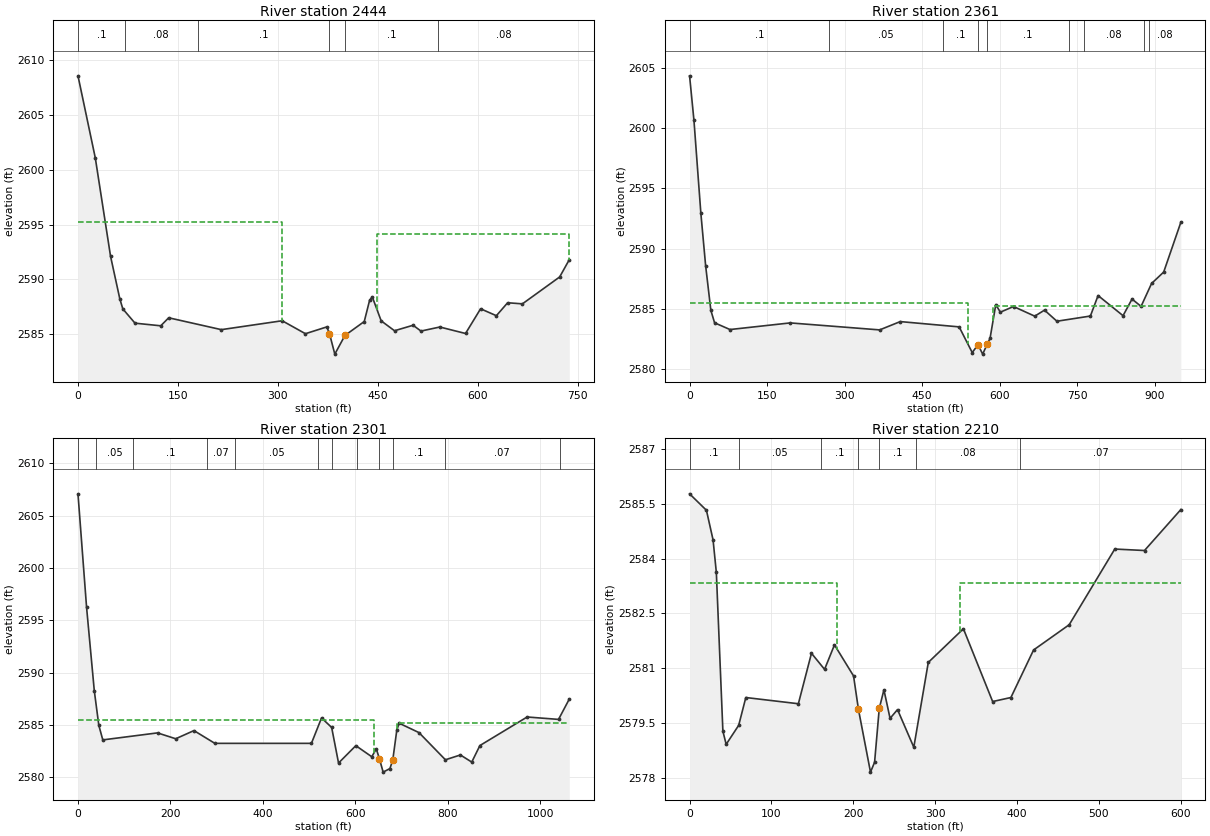
Type RM Length L Ch R = 1 ,2444    ,96.8,83.5,71.8
XS GIS Cut Line= 4
2294577.56715852 538771.71252458 2294863.0929021538610.754582606
2294874.75309034 538468.333711972294686.01737169538279.848793437
#Sta/Elev= 30
       0 2608.55      26 2601.07    48.9 2592.11    62.7 2588.26    67.3 2587.32
    85.6 2586.02   124.2 2585.78   136.2 2586.51   215.2 2585.43   306.5 2586.24
   341.4 2585.06   373.5 2585.68   377.5 2585.07   385.5  2583.2   400.7  2584.9
   429.7 2586.17   437.7  2588.1   441.7 2588.42   455.1 2586.23   475.1 2585.33
     503 2585.83   514.8  2585.3   543.1 2585.67   581.7 2585.08   604.3 2587.33
     628  2586.7   644.9 2587.88   667.1 2587.78     723 2590.23   737.4  2591.8
#Mann= 6 ,-1,0
       0      .1       0      70     .08       0     180      .1       0
   377.5    .045       0   400.7      .1       0  540.67     .08       0
#XS Ineff= 2 , 0
          306.86 2595.24  449.08         2594.13
Permanent Ineff=
       F       F
Bank Sta=377.5,400.7
XS Rating Curve= 0 ,0
Exp/Cntr(USF)=0,0
Exp/Cntr=0.5,0.3

Type RM Length L Ch R = 1 ,2361    ,56,60.2,57.8
XS GIS Cut Line= 4
2294774.32583997 539032.810026972294988.02642028538587.800043855
2294799.68474464538333.7101749592294680.01298571538259.208354718
#Sta/Elev= 30
       0 2604.33     8.5 2600.63    21.8 2592.95    31.1 2588.57    41.2 2584.87
    48.4 2583.84    78.2 2583.28   194.8 2583.83   367.9 2583.25   407.8 2583.94
   521.8  2583.5   547.1 2581.37   558.3 2582.02   567.3 2581.24   576.42582.095
   581.6 2582.55   592.7 2585.35   601.5 2584.72     627 2585.19   668.1 2584.39
     687 2584.89     711 2583.97   775.8  2584.4   790.7  2586.1     839 2584.43
   856.4 2585.81   873.9  2585.2   894.2  2587.1   917.7 2588.05   950.9 2592.18
#Mann= 9 ,-1,0
       0      .1       0     270     .05       0     490      .1       0
   558.3    .045       0   576.4      .1       0  733.66     .07       0
  763.66     .08       0  879.94     .07       0  889.94     .08       0
#XS Ineff= 2 , 0
          538.21  2585.5  587.44          2585.2
Permanent Ineff=
       F       F
Bank Sta=558.3,576.4
XS Rating Curve= 0 ,0
Exp/Cntr(USF)=0,0
Exp/Cntr=0.5,0.3

Type RM Length L Ch R = 1 ,2301    ,91.2,91,90.3
XS GIS Cut Line= 4
2294817.71576572539094.1748513242295048.43425539538579.581250754
2294851.53027766538304.4370587172294705.25386544538237.330146286
#Sta/Elev= 30
       0  2607.1    18.6 2596.25    35.3 2588.28    45.1 2584.97    53.7 2583.58
   172.1 2584.25   211.5 2583.69     251 2584.47   296.2 2583.25   505.2 2583.25
   527.1 2585.68     549 2584.77   563.9 2581.37   601.3 2583.03   635.8 2581.97
   645.6 2582.72   652.42581.775   660.4  2580.5   675.1 2580.84   681.3 2581.67
   689.9 2584.49   694.8 2585.18   737.9 2584.28   795.2 2581.68   827.6 2582.14
   852.2 2581.46   869.8 2583.04     972 2585.77    1040 2585.54  1063.2 2587.48
#Mann= 12 ,-1,0
       0      .1       0      40     .05       0     120      .1       0
     280     .07       0     340     .05       0     520      .1       0
     550     .05       0  603.95      .1       0   652.4    .045       0
   681.3      .1       0  793.95     .07       0 1042.29     .08       0
#XS Ineff= 2 , 0
          640.55  2585.5  691.17          2585.2
Permanent Ineff=
       F       F
Bank Sta=652.4,681.3
XS Rating Curve= 0 ,0
Exp/Cntr(USF)=0,0
Exp/Cntr=0.5,0.3

Type RM Length L Ch R = 1 ,2210    ,,,
XS GIS Cut Line= 4
2295065.04242671538649.7831739952295077.01010309538463.656473628
2294987.73998379538346.1409750342294752.99615248 538221.07660799
#Sta/Elev= 30
       0 2585.77    20.6 2585.32    28.7 2584.51    32.7 2583.62    40.7 2579.28
    44.7 2578.92      60 2579.44    68.7  2580.2   132.9 2580.03   148.9 2581.41
   164.9 2580.97     177 2581.64   200.3 2580.79   206.32579.873     221 2578.16
     226 2578.43   231.7  2579.9   237.4 2580.41   244.9 2579.63     254 2579.87
   273.9 2578.84   291.6 2581.16   334.5 2582.08   370.2 2580.09   392.5  2580.2
   420.2  2581.5   463.7 2582.19   519.4 2584.26   555.7 2584.22   600.1 2585.34
#Mann= 7 ,-1,0
       0      .1       0      60     .05       0     160      .1       0
   206.3    .045       0   231.7      .1       0  276.51     .08       0
  404.09     .07       0
#XS Ineff= 2 , 0
          180.58 2583.32  330.05         2583.34
Permanent Ineff=
       F       F
Bank Sta=206.3,231.7
XS Rating Curve= 0 ,0
Exp/Cntr(USF)=0,0
Exp/Cntr=0.3,0.1
LCMann Table=0

Chan Stop Cuts=-1
Use User Specified Reach Order=0
Composite Channel Slope=5